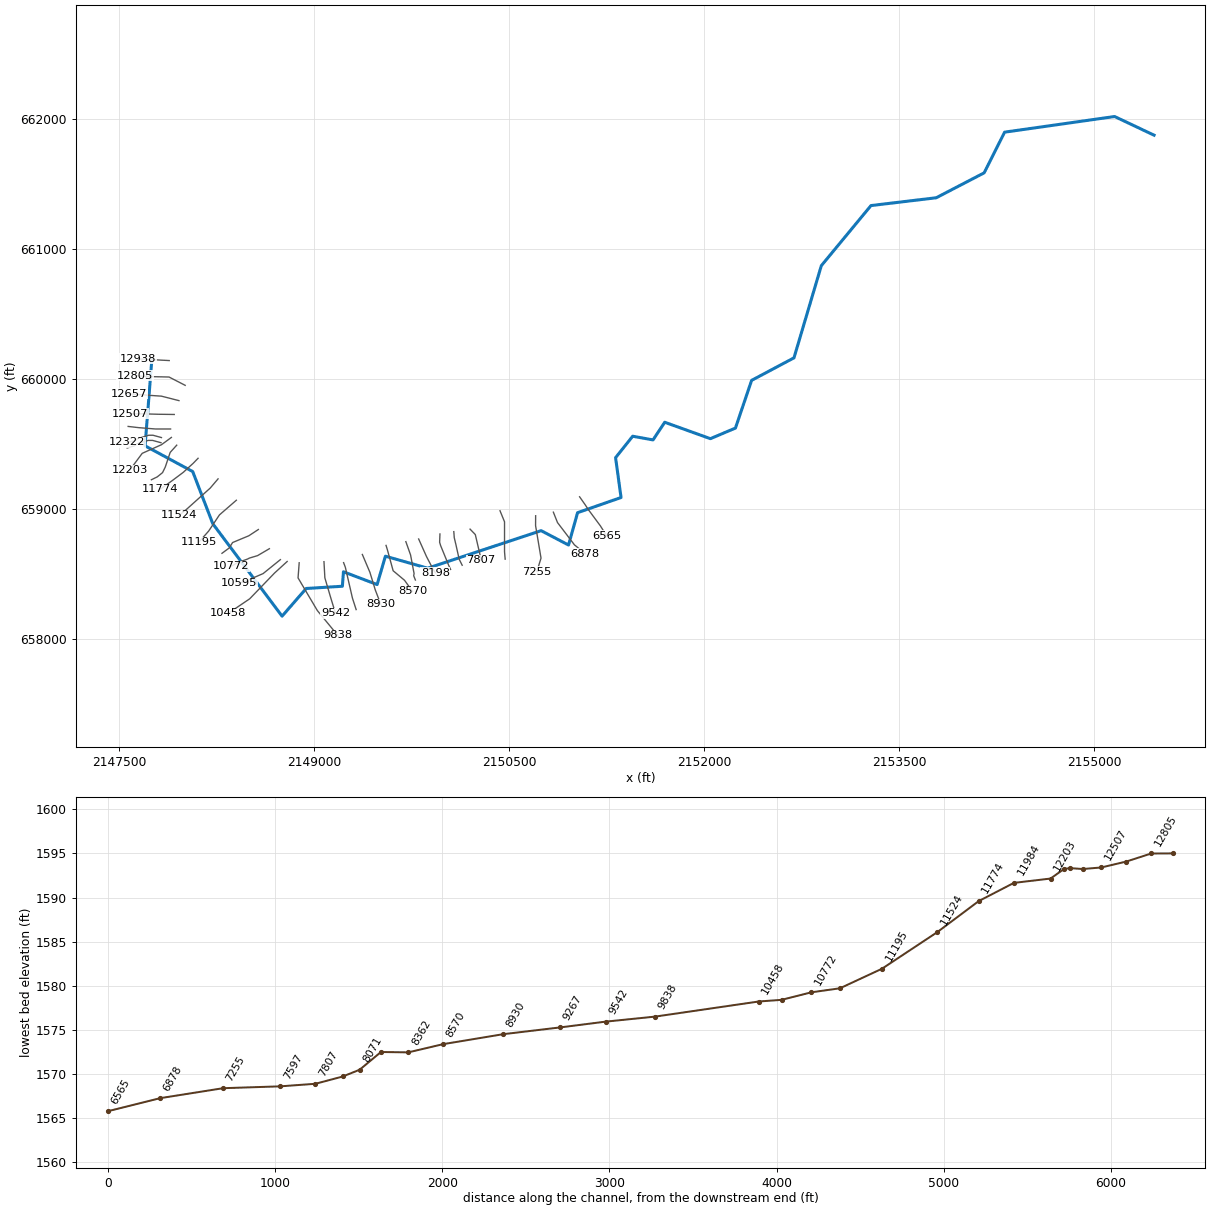
--- COWRN.prj (project) ---

Proj Title=COWRN
Current Plan=p01
Default Exp/Contr=0,0
English Units
Geom File=g01
Flow File=f01
Plan File=p01
BEGIN DESCRIPTION:
---------- MODELED AS PART OF WVEMD CTP PROGRAM, 2023----------
Stream Name: Cow Run
Flood Zone:  AFH
Upshur County, WV
HEC-RAS Version: RAS 6.3
Vertical Datum: NAVD88
Projection: NAD 1983 StatePlane West Virginia S FIPS 4702 (US Feet)
Terrain: 1-meter LIDAR (FEMA Region III 3DEP collected 2016-2018)
Land Use: 2019 NLCD
Hydrologic Method:
WV SIR2010-5033 regression equations
Additional Model Notes:
None
END DESCRIPTION:
DSS Export Rating Curves= 0
DSS Export Rating Curve Sorted= 0
DSS Export Volume Flow Curves= 0
DXF OffsetX= 0
DXF OffsetY= 0
DXF ScaleX= 0
DXF ScaleY= 0

--- COWRN.p01 (plan) ---

Plan Title=Floodplain
Program Version=6.30
Short Identifier=Floodplain
Geom File=g01
Flow File=f01
Subcritical Flow
K Sum by GR= 0
Std Step Tol= 0.01
Critical Tol= 0.01
Num of Std Step Trials= 20
Max Error Tol= 0.3
Flow Tol Ratio= 0.001
Split Flow NTrial= 30
Split Flow Tol= 0.02
Split Flow Ratio= 0.02
Log Output Level= 0
Friction Slope Method= 1
Unsteady Friction Slope Method= 2
Unsteady Bridges Friction Slope Method= 1
Parabolic Critical Depth
Global Vel Dist= 0 , 0 , 0
Global Log Level= 0
CheckData=False
Encroach Param=-1 ,0,0, 0
Mapping Interval=1HOUR
Computation Time Step Use Courant=        0
Computation Time Step Use Time Series=    0
Computation Time Step Count To Double=0
Computation Time Step Max Doubling=0
Computation Time Step Max Halving=0
Computation Time Step Residence Courant=0
Run HTab= 0
Run UNet= 0
Run Sediment= 0
Run PostProcess= 0
Run WQNet= 0
Run RASMapper=-1
UNET Theta= 0
UNET Theta Warmup= 0
UNET ZTol= 0
UNET ZSATol= 0
UNET MxIter= 0
UNET Max Iter WO Improvement= 0
UNET MaxInSteps= 0
UNET DtIC= 0
UNET DtMin= 0
UNET MaxCRTS= 0
UNET WFStab= 0
UNET SFStab= 0
UNET WFX= 1
UNET SFX= 1
UNET Gravity=32.17405
UNET 1D Methodology=Finite Difference
UNET DSS MLevel= 1
UNET Pardiso=0
UNET DZMax Abort= 0
UNET Use Existing IB Tables= 0
UNET Froude Reduction=False
UNET Froude Limit= 0
UNET Froude Power= 0
UNET D1 Cores= 0
UNET WindReference=Eulerian
UNET WindDragFormulation=Hsu (1988)
UNET D2 Coriolis=0
UNET D2 Cores= 0
UNET D2 Theta= 1
UNET D2 Theta Warmup= 1
UNET D2 Z Tol= 0.01
UNET D2 Volume Tol= 0.01
UNET D2 Max Iterations= 20
UNET D2 Equation= 0
UNET D2 RampUpFraction=0.1
UNET D2 TimeSlices= 1
UNET D2 Turbulence Formulation=Non-Conservative (original)
UNET D2 Eddy Viscosity=0.3
UNET D2 Transverse Eddy Viscosity=0.1
UNET D2 Smagorinsky Mixing=0
UNET D2 BCVolumeCheck=0
UNET D2 Cores=0
UNET D2 SolverType=PARDISO (Direct)
UNET D2 Minimum Iterations= 3
UNET D2 Maximum Iterations= 30
UNET D2 Restart Number= 10
UNET D2 Relaxation Coeff=1.3
UNET D2 SOR Precondition Iterations= 10
UNET D2 ILUT Maximum Fill= 8
UNET D2 ILUT Tolerance=1E-08
UNET D2 Convergence Tolerance=0.00001
UNET D1D2 MaxIter= 0
UNET D1D2 ZTol=0.01
UNET D1D2 QTol=0.1
UNET D1D2 MinQTol=1
Write IC File= 0
Write IC File at Fixed DateTime=0
Write IC File at Sim End=0
Echo Input=False
Echo Parameters=False
Echo Output=False
Write Detailed= 0
HDF Write Warmup=0
HDF Write Time Slices=0
HDF Flush=0
HDF Compression= 1
HDF Chunk Size= 1
HDF Spatial Parts= 1
HDF Use Max Rows=0
HDF Fixed Rows= 1
Calibration Method= 0
Calibration Iterations= 20
Calibration Max Change=0.05
Calibration Tolerance=0.2
Calibration Maximum=1.5
Calibration Minimum=0.5
Calibration Optimization Method= 1
WQ AD Non Conservative
WQ ULTIMATE=-1
WQ Max Comp Step=1HOUR
WQ Output Interval=15MIN
WQ Output Selected Increments= 0
WQ Output face flow=0
WQ Output face velocity=0
WQ Output face area=0
WQ Output face dispersion=0
WQ Output cell volume=0
WQ Output cell surface area=0
WQ Output cell continuity=0
WQ Output cumulative cell continuity=0
WQ Output face conc=0
WQ Output face dconc_dx=0
WQ Output face courant=0
WQ Output face peclet=0
WQ Output face adv mass=0
WQ Output face disp mass=0
WQ Output cell mass=0
WQ Output cell source sink temp=0
WQ Output nsm pathways=0
WQ Output nsm derived pathways=0
WQ Create Restart=0
WQ Fixed Restart=0
WQ System Summary=0
WQ Write To DSS=0
Sorting and Armoring Iterations= 10
XS Update Threshold= 0.02
Bed Roughness Predictor= 0
Hydraulics Update Threshold= 0.02
Energy Slope Method= 1
Volume Change Method= 1
Sediment Retention Method= 0
Sediment TS Multiplier= 1
Warm Up Method= 0
XS Weighting Method= 0
Number of US Weighted Cross Sections= 1
Number of DS Weighted Cross Sections= 1
Upstream XS Weight=0
Main XS Weight=1
Downstream XS Weight=0
Number of DS XS's Weighted with US Boundary= 1
Upstream Boundary Weight= 1
Weight of XSs Associated with US Boundary= 0
Number of US XS's Weighted with DS Boundary= 1
Downstream Boundary Weight= 0.5
Weight of XSs Associated with DS Boundary= 0.5
Percentile Method= 0
Sediment Output Level= 3
Mass or Volume Output= 0
Output Increment Type= 1
Profile and TS Output Increment= 1
Transport Output Increment 1
XS Output Flag= 0
XS Output Increment= 10
Read HDF5 Sediment Hotstart= 0
Sediment Hotstart Type= 0
Write Gradation File= 0
Read Gradation Hotstart= 0
Write HDF5 File= 1
Write Binary Output= 1
Write DSS Sediment File= 0
DSS Sediment Output Type= 1
SV Curve= 0
Specific Gage Flag= 0
Subcell Erosion Methods= 0
Subcell Deposition Methods= 0
Advection Scheme= 1
Matrix Solver= 0
Implicit Weighting Factor= 1
Maximum Outer Loop Convergence Iterations= 5
Convergence Maximum Absolute= 0.001
Convergence RMSE= 0.0001
Grain Fractions Max Abs Error= 0.001
Max Subgrid Regions= 1
Max Subgrid Length Scale= 3.402823E+38
Initial Layer Thickness= 3.402823E+38
Min Layer Thickness= 3.402823E+38
Max Layer Thickness= 3.402823E+38
Number of Layers= 5

--- COWRN.f01 (steady flow) ---

Flow Title=Flows
Program Version=6.31
Number of Profiles= 1
Profile Names=01pct
River Rch & RM=COWRN,Main,12938
     760
River Rch & RM=COWRN,Main,9838
     985
River Rch & RM=COWRN,Main,7255
    1100
River Rch & RM=COWRN,Main,3497
    1230
Boundary for River Rch & Prof#=COWRN,Main            , 1
Up Type= 0
Dn Type= 3
Dn Slope=0.00275
DSS Import GetInterval= 0
DSS Import GetPeak= 0
DSS Import FillOption= 0

--- COWRN.g01 (geometry) ---

Geom Title=Geometry
Program Version=6.31

River Reach=COWRN           ,Main
Reach XY= 30
2147749.65712494660156.6290297022147696.93400002659485.828000009
2148063.53800002 659287.946000012148218.26700005658886.143000022
2148751.30399999658174.9399999982148936.91000003658387.989000008
2149215.43400002658405.1309999972149223.73200004658516.391000003
2149482.82500002      658418.2942149546.61100003658636.494000018
2149871.75100002658544.1200000052150745.03699999658832.974000007
2150955.96800001658722.4580000192151025.50599998658971.449000016
2151360.08900002659088.0890000162151318.08000001659394.800000012
2151449.63000004 659559.745000022151606.33300003659531.472000003
2151696.27400002659667.3420000082152047.76900002659540.886000022
     2152240.587 659622.586000012152365.06800002659989.791999996
     2152691.037660162.978000015     2152901.396660872.263999999
     2153283.625661334.9910000122153785.78600003661394.998999998
2154154.42200004661586.643000022     2154312.213661899.993000016
2155158.85699999662020.2390000082155462.33527599  661876.6930684

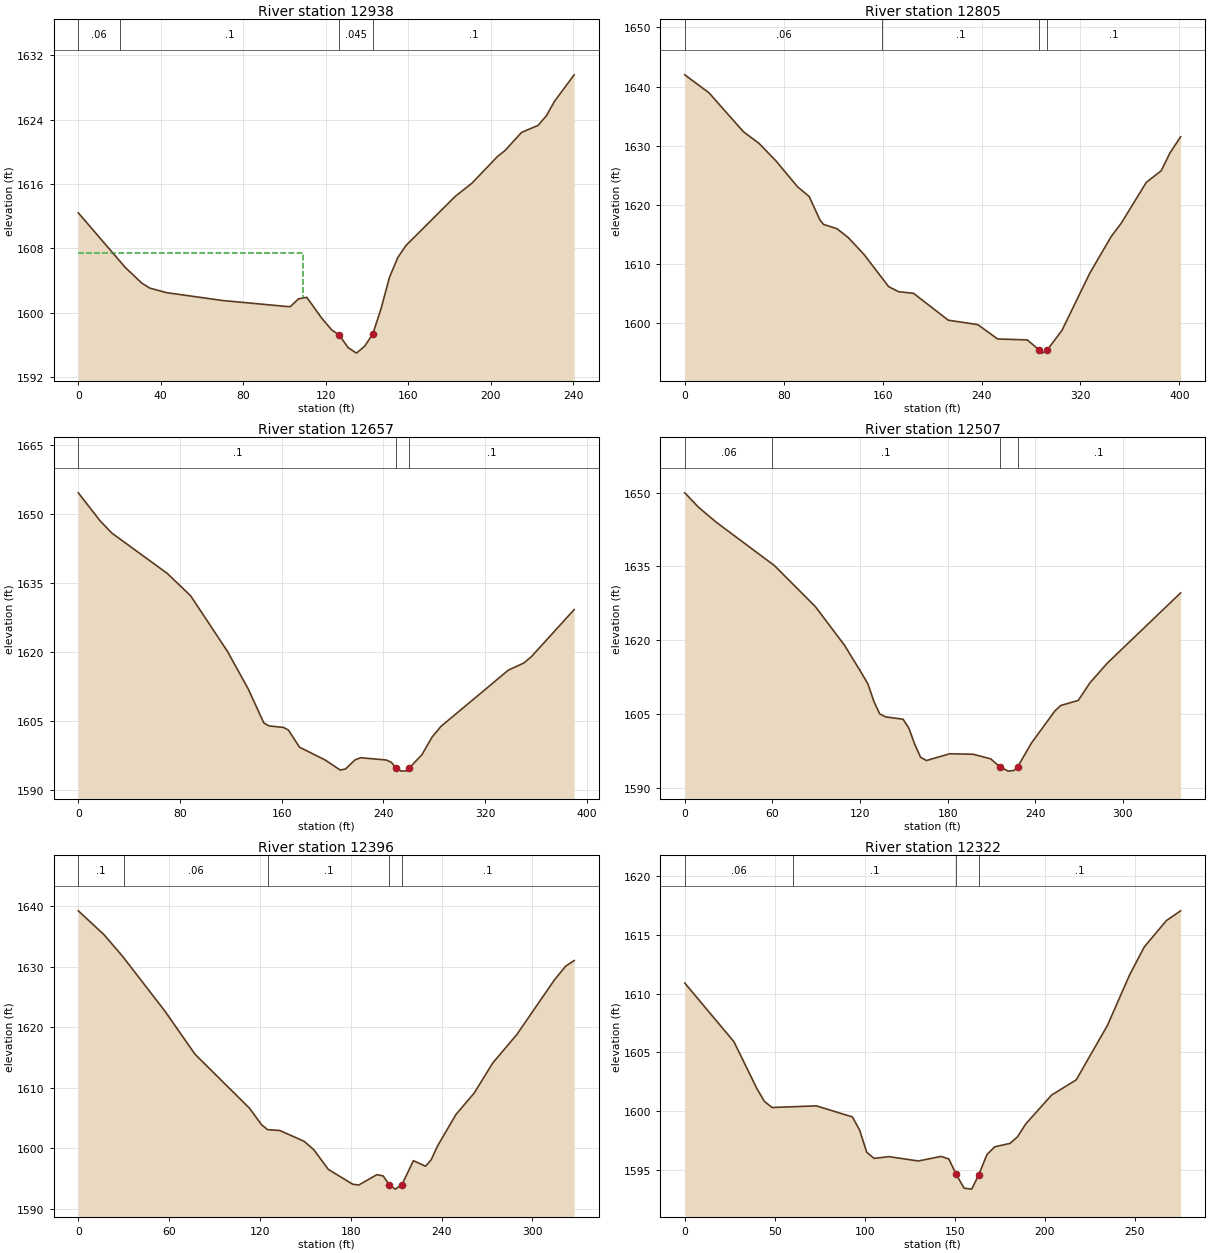
Type RM Length L Ch R = 1 ,12938   ,131.3,132.8,131.4
XS GIS Cut Line= 2
2147882.86522358660142.1356373392147642.69496531660154.898308068
#Sta/Elev= 30
       0 1612.42    22.7 1605.66    30.7 1603.71    34.7 1603.07    42.8 1602.51
    70.1 1601.53   101.2 1600.79   102.8 1600.77   106.8 1601.74   110.8 1601.93
   118.1 1599.33   122.9 1597.88   126.5 1597.26   130.9 1595.68   134.9    1595
   138.9 1595.86   142.9 1597.42   146.9 1600.58   150.9 1604.39   154.9 1606.84
   158.9 1608.36   182.9 1614.48     191 1616.12   203.2 1619.39   206.9 1620.14
     215 1622.41     223 1623.28     227 1624.46     231 1626.28240.5091 1629.56
#Mann= 4 ,-1,0
       0     .06       0      20      .1       0   126.5    .045       0
   142.9      .1       0
#XS Ineff= 2 , 0
          109.15 1607.49
Permanent Ineff=
       F       F
Bank Sta=126.5,142.9
XS Rating Curve= 0 ,0
Exp/Cntr(USF)=0,0
Exp/Cntr=0.3,0.1

Type RM Length L Ch R = 1 ,12805   ,147.5,148.6,147
XS GIS Cut Line= 4
2148005.62215735659951.4778625472147881.35320711660015.439822233
2147696.32039516660019.5516624992147620.47978582660026.861600748
#Sta/Elev= 30
       0 1641.99    19.6 1638.95    47.4 1632.38    60.1  1630.4    73.6 1627.49
    91.1  1623.1   100.6 1621.44   109.3 1617.48   112.2 1616.73   123.1    1616
   132.1 1614.52   144.9 1611.67   164.9 1606.21     173 1605.36     185 1605.09
   213.1 1600.55     237  1599.8     253 1597.38     277 1597.22   286.5 1595.55
     289 1594.99     293  1595.5     305 1598.82   327.6 1608.52   344.8 1614.66
   353.1 1616.97   373.2 1623.82   385.3 1625.79   392.4 1628.81     401 1631.53
#Mann= 4 ,-1,0
       0     .06       0  159.76      .1       0   286.5    .045       0
     293      .1       0
Bank Sta=286.5,293
XS Rating Curve= 0 ,0
Exp/Cntr(USF)=0,0
Exp/Cntr=0.3,0.1

Type RM Length L Ch R = 1 ,12657   ,148.6,149.6,149.4
XS GIS Cut Line= 3
2147957.73743225659833.8025500942147822.76709862659868.189896242
2147572.59915538659885.383569317
#Sta/Elev= 30
       0 1654.53    17.2 1648.42    26.4 1645.78    69.9 1637.04    88.3 1632.18
   117.2 1620.14   133.7  1611.9   145.9 1604.55   149.9 1603.91   161.4 1603.57
   165.2 1603.02     174 1599.27     194 1596.52     206 1594.32   210.2 1594.55
   217.7 1596.54   222.1 1596.99   242.1  1596.5   246.1 1596.02   250.1 1594.71
   254.1 1594.08   258.2 1594.15  260.161594.729   270.2 1597.62   278.2 1601.46
   285.2 1603.79   338.3 1616.03   350.4 1617.56   356.3 1618.93     390 1629.17
#Mann= 3 ,-1,0
       0      .1       0   250.1    .045       0  260.16      .1       0
Bank Sta=250.1,260.16
XS Rating Curve= 0 ,0
Exp/Cntr(USF)=0,0
Exp/Cntr=0.3,0.1

Type RM Length L Ch R = 1 ,12507   ,112.1,111.5,110.6
XS GIS Cut Line= 4
2147921.63071879659727.2017770332147794.39753804659728.921144341
2147672.32245922659732.3598789552147582.05567558659731.500195302
#Sta/Elev= 30
       0 1649.96     9.5    1647    21.5    1644    61.5 1635.15    89.5 1626.82
   109.5 1618.94   121.5 1613.12   125.5 1611.08   129.5 1607.59   133.5 1605.04
   137.5 1604.44   149.5 1603.96   153.5 1602.12   157.5 1598.86   161.5 1596.23
   165.5 1595.56   181.5 1596.94   197.5 1596.84   209.5 1595.91   215.7 1594.31
   221.5 1593.41   225.5 1593.54   228.1 1594.35   237.5 1599.15   253.5 1605.65
   257.5 1606.75   269.5 1607.78   277.5 1611.36   289.5 1615.39   339.6 1629.63
#Mann= 4 ,-1,0
       0     .06       0      60      .1       0   215.7    .045       0
   228.1      .1       0
Bank Sta=215.7,228.1
XS Rating Curve= 0 ,0
Exp/Cntr(USF)=0,0
Exp/Cntr=0.3,0.1

Type RM Length L Ch R = 1 ,12396   ,70.1,74.3,79.8
XS GIS Cut Line= 4
2147893.26115822 659615.442902052147778.06354862 659615.44290205
2147648.25131691659625.7591058952147566.58136981659635.215626086
#Sta/Elev= 30
       0 1639.26    17.1 1635.28    29.1 1631.78    57.1 1622.71    77.1 1615.54
   113.1 1606.61   121.1 1603.87   125.1 1603.06   133.1 1602.93   149.2 1601.14
   155.7 1599.71   165.2 1596.49   181.3 1594.04   185.3 1593.91   197.3 1595.63
   201.4 1595.41   205.4 1593.97   209.4 1593.23  213.821593.963   221.4 1597.94
   229.4 1597.02   233.1 1598.07   237.4  1600.4   249.5 1605.57   261.6 1609.14
   273.8 1614.09   289.8 1618.83   314.5 1627.81     322 1630.11   327.6 1631.04
#Mann= 5 ,-1,0
       0      .1       0      30     .06       0   125.2      .1       0
   205.4    .045       0  213.82      .1       0
Bank Sta=205.4,213.82
XS Rating Curve= 0 ,0
Exp/Cntr(USF)=0,0
Exp/Cntr=0.3,0.1

Type RM Length L Ch R = 1 ,12322   ,37.3,36.6,36.3
XS GIS Cut Line= 6
2147822.90054331659549.5070736712147758.11562183659567.322927078
2147724.10353806659567.3229270782147639.88314013659541.408958486
2147617.20841761659525.2127281162147560.52161132 659512.25574382
#Sta/Elev= 30
       0  1610.9    27.3  1605.9    40.2 1601.86    44.3  1600.8    48.5 1600.29
    73.1 1600.43    93.1 1599.49    97.1 1598.38   101.1 1596.47   105.2 1595.95
   113.4  1596.1   129.8 1595.73   142.4 1596.12   146.7  1595.9   150.81594.592
   155.2 1593.41   159.4 1593.33   163.21594.504   167.9 1596.28   172.2 1596.94
   180.7 1597.23   184.9  1597.8   189.4 1598.88   203.8 1601.35   217.5 1602.65
   234.8 1607.28   247.1 1611.58   255.3 1613.98   267.6 1616.23   275.5 1617.06
#Mann= 4 ,-1,0
       0     .06       0      60      .1       0   150.8    .045       0
   163.2      .1       0
Bank Sta=150.8,163.2
XS Rating Curve= 0 ,0
Exp/Cntr(USF)=0,0
Exp/Cntr=0.3,0.1

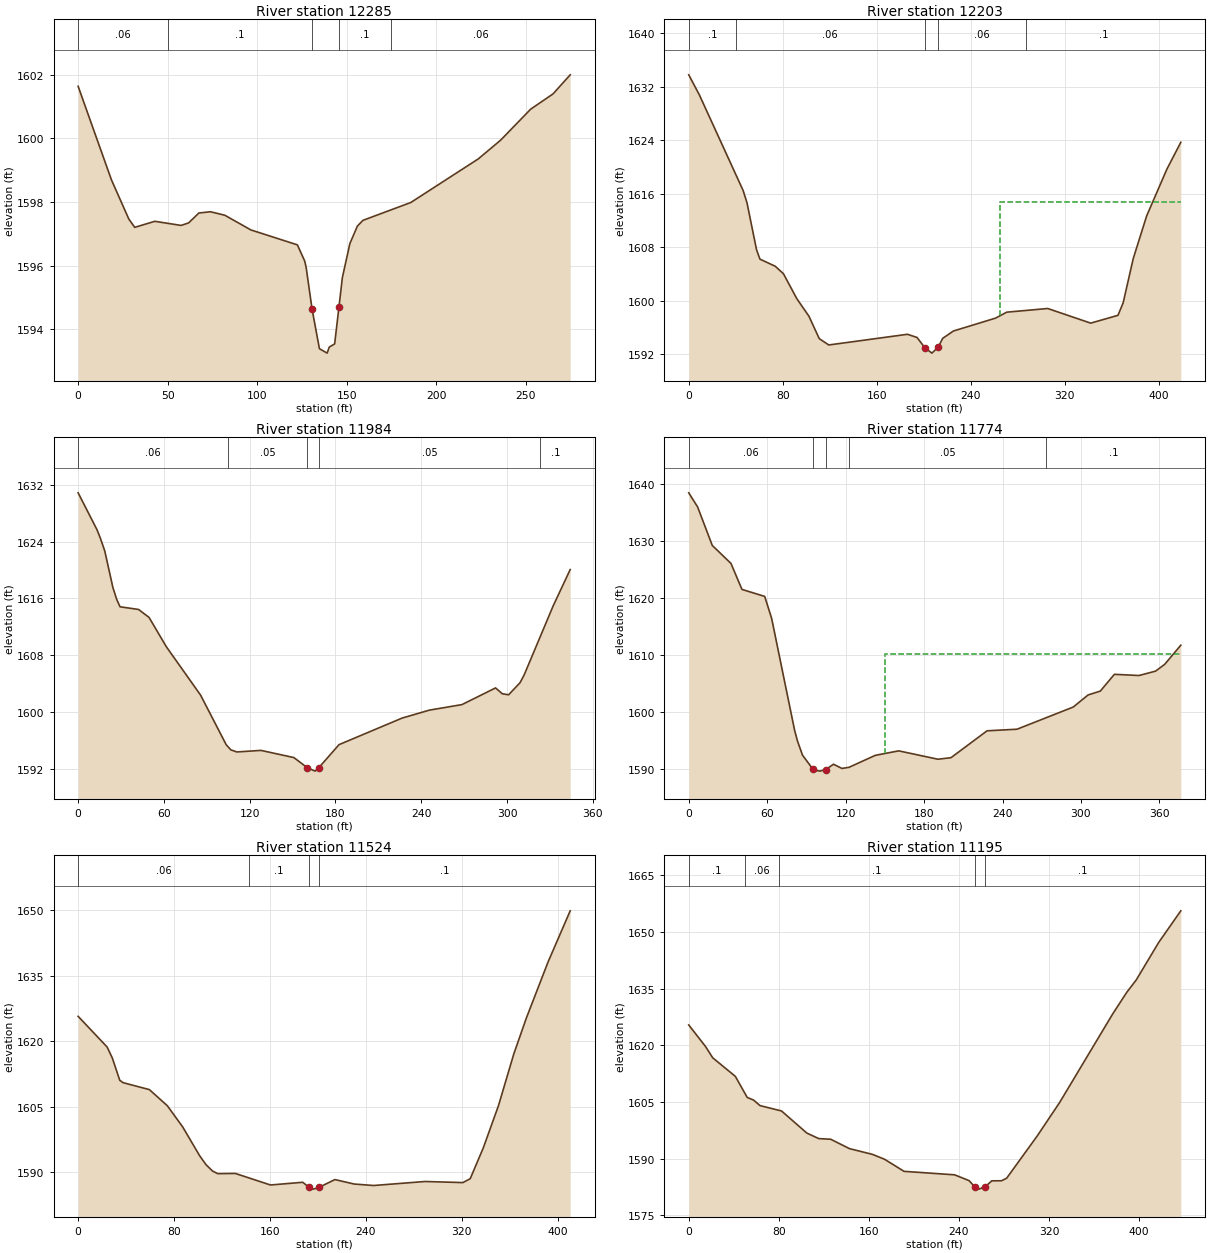
Type RM Length L Ch R = 1 ,12285   ,79.2,81.6,81.6
XS GIS Cut Line= 6
2147819.66129724659509.8263092652147754.87637576659527.642162672
2147720.86429198659527.6421626722147636.64389406 659501.72819408
2147613.96917154 659485.531963712147558.90198828 659469.33573334
#Sta/Elev= 30
       0 1601.63    18.6 1598.69    28.3 1597.46    31.6  1597.2    42.8 1597.39
    57.5 1597.26    61.7 1597.34    67.4 1597.65    73.9 1597.69    81.9 1597.58
    96.4 1597.12   122.4 1596.65   126.5 1596.14   127.3 1595.94   130.6 1594.63
   134.7 1593.39     139 1593.25   140.2 1593.44   143.2 1593.54   145.61594.693
   147.5 1595.62   151.7 1596.69   155.9 1597.24     159 1597.42   185.7 1597.98
   223.4 1599.35   235.9 1599.94   252.6 1600.91   265.1 1601.39   274.7 1601.99
#Mann= 5 ,-1,0
       0     .06       0      50      .1       0   130.6    .045       0
   145.6      .1       0   174.4     .06       0
Bank Sta=130.6,145.6
XS Rating Curve= 0 ,0
Exp/Cntr(USF)=0,0
Exp/Cntr=0.3,0.1

Type RM Length L Ch R = 1 ,12203   ,209.9,219.3,225.5
XS GIS Cut Line= 4
2147899.48389524659550.5404694142147823.65979698659494.832968653
2147675.10646162659428.2934538562147578.39205057659298.309285414
#Sta/Elev= 30
       0 1633.81     9.1 1630.78    46.3 1616.49    49.6 1614.64    57.7 1607.63
    60.6 1606.22    73.6 1605.16    80.6 1604.04      92  1600.3   102.3 1597.68
   111.1 1594.32   119.2 1593.37   186.2 1594.97   194.3  1594.5   200.9 1592.99
   200.9 1592.98     207 1592.15   212.31593.037   216.2 1594.36   225.3 1595.46
   261.2 1597.39   270.7 1598.28   305.6 1598.83   342.2 1596.64   365.4 1597.81
   369.8 1599.67   378.4  1606.3   389.8 1612.68     407 1619.67   418.9 1623.71
#Mann= 5 ,-1,0
       0      .1       0      40     .06       0   200.9    .045       0
   212.3     .06       0  286.86      .1       0
#XS Ineff= 2 , 0
                          265.07         1614.81
Permanent Ineff=
       F       F
Bank Sta=200.9,212.3
XS Rating Curve= 0 ,0
Exp/Cntr(USF)=0,0
Exp/Cntr=0.3,0.1

Type RM Length L Ch R = 1 ,11984   ,215.5,210.1,205.1
XS GIS Cut Line= 6
2147940.49080552659490.9643922112147890.19931178659435.256891451
2147852.28726265659322.2944593522147831.39694986659279.740118493
2147791.16375487659247.2440763832147745.51455286659224.806333021
#Sta/Elev= 30
       0 1630.86    13.2 1625.66    15.6 1624.44    18.6 1622.69    24.3 1617.53
      27 1615.84    29.3 1614.81    42.3 1614.43    49.6 1613.31    61.7 1609.18
    85.7 1602.35   103.6 1595.37   106.8 1594.66     111 1594.36   127.9 1594.58
   150.9 1593.57   160.4 1592.13   165.8 1591.66   168.21592.109   182.5 1595.39
   226.6 1599.13   245.7 1600.25   268.5 1601.03     292 1603.38   296.7 1602.56
   301.1 1602.41   309.1 1604.11     312 1605.21   332.3 1614.94   344.2 1620.05
#Mann= 5 ,-1,0
       0     .06       0  105.05     .05       0   160.4    .045       0
   168.2     .05       0  323.33      .1       0
Bank Sta=160.4,168.2
XS Rating Curve= 0 ,0
Exp/Cntr(USF)=0,0
Exp/Cntr=0.3,0.1

Type RM Length L Ch R = 1 ,11774   ,251,250.4,250.5
XS GIS Cut Line= 5
2148104.86378552 659390.094937062148068.20128658659352.304361231
2147991.49205804659282.3635940262147906.13020762659218.329897996
2147814.14759446659152.291098808
#Sta/Elev= 30
       0 1638.47     6.8 1635.98      18 1629.23    32.3 1626.07    40.7 1621.51
    58.1 1620.28    63.4 1616.43      81 1596.74    83.2 1594.87      87 1592.41
   95.121589.899   100.2  1589.6   104.8 1589.87   110.7 1590.81   117.2 1590.07
   122.6 1590.27   142.7 1592.37   160.6 1593.16   190.6 1591.69   200.6 1591.96
   228.2 1596.68   251.1 1596.96   294.1 1600.85   305.5 1602.98   314.8 1603.65
   325.6  1606.6   344.4 1606.39   357.1 1607.16   364.1 1608.36   376.4 1611.71
#Mann= 5 ,-1,0
       0     .06       0   95.12    .045       0   104.8     .06       0
  122.65     .05       0  273.17      .1       0
#XS Ineff= 2 , 0
                          149.86         1610.15
Permanent Ineff=
       F       F
Bank Sta=95.12,104.8
XS Rating Curve= 0 ,0
Exp/Cntr(USF)=0,0
Exp/Cntr=0.3,0.1

Type RM Length L Ch R = 1 ,11524   ,323.7,328.8,328.7
XS GIS Cut Line= 4
2148258.67359081659231.5789009142148198.49573505659160.893800498
2148013.18614747658994.6882941122147959.69472013658951.704111426
#Sta/Elev= 30
       0 1625.69    24.2 1618.64    28.5 1616.13    34.7 1611.03    37.5 1610.47
    59.4 1608.88    74.4 1605.18    87.2 1600.32   101.3 1593.73   106.7 1591.64
   112.1  1590.2   116.4  1589.6   131.1 1589.65   160.4    1587   187.3 1587.62
  192.561586.491   196.2 1586.05  201.091586.484   214.2 1588.24   230.2 1587.22
   246.4 1586.88   289.4  1587.8   320.9 1587.55     327 1588.44   337.9  1595.5
   350.6 1605.21   363.3 1617.01   373.8 1625.27   391.9 1638.13   410.4 1649.89
#Mann= 4 ,-1,0
       0     .06       0  142.83      .1       0  192.56    .045       0
  201.09      .1       0
Bank Sta=192.56,201.09
XS Rating Curve= 0 ,0
Exp/Cntr(USF)=0,0
Exp/Cntr=0.3,0.1

Type RM Length L Ch R = 1 ,11195   ,257.6,251,245.5
XS GIS Cut Line= 4
2148399.44304778659067.161303674   2148269.48859658954.466422322
2148185.65128101658829.0425230872148109.65425019658743.873436832
#Sta/Elev= 30
       0 1625.41    14.9  1619.7    21.3 1616.71    41.4 1611.79    51.9 1606.23
    57.6 1605.51    63.3 1604.05    82.4 1602.63   104.9 1596.77   115.5 1595.31
   126.1 1595.14   142.7 1592.66   163.2 1591.13   173.9 1589.84   191.2 1586.64
   236.1 1585.72   248.9 1584.19  253.841582.606   257.5 1581.93   263.3 1582.54
   269.1 1584.13   277.7 1584.14   282.3 1584.81   309.4 1595.98   329.5 1604.93
   376.3 1628.23     389 1634.06   397.5 1637.37   417.3 1647.24     437 1655.64
#Mann= 5 ,-1,0
       0      .1       0      50     .06       0      80      .1       0
  253.84    .045       0   263.3      .1       0
Bank Sta=253.84,263.3
XS Rating Curve= 0 ,0
Exp/Cntr(USF)=0,0
Exp/Cntr=0.3,0.1

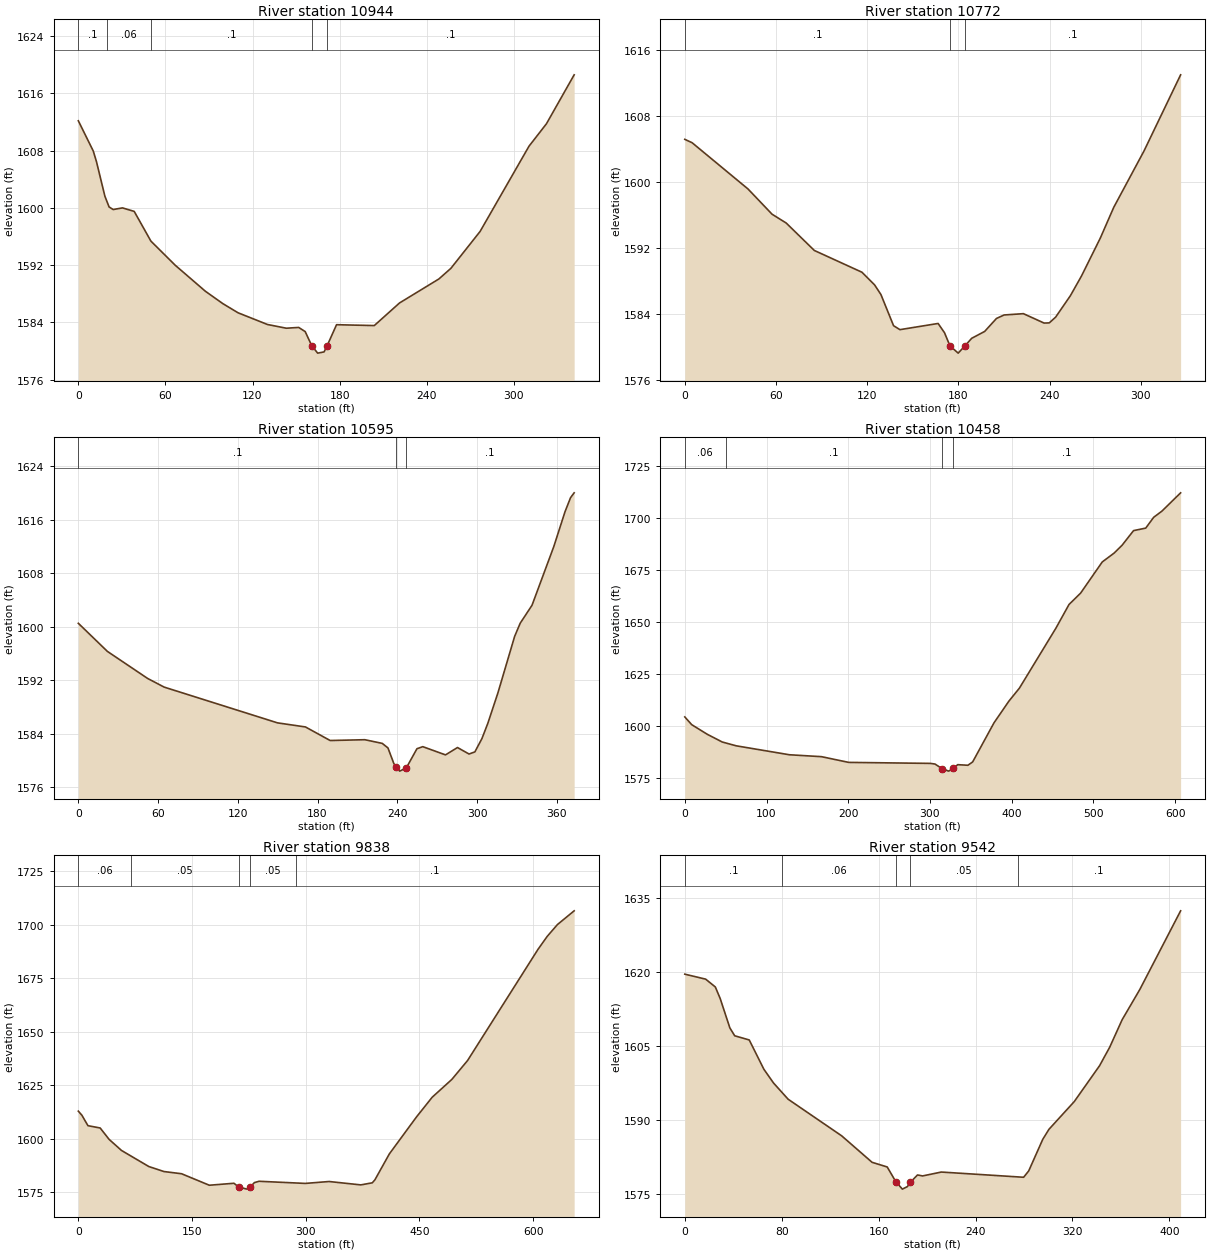
Type RM Length L Ch R = 1 ,10944   ,170.5,171.6,171.8
XS GIS Cut Line= 5
2148568.78234581658841.8728100972148495.66625106658793.825090691
2148370.32437435658741.5993087282148344.55965525658699.818683157
2148288.85215449658658.734401346
#Sta/Elev= 30
       0 1612.18    10.3 1607.95    12.5 1606.47    18.3 1601.64    21.2 1600.14
      24 1599.78    30.4 1600.01    38.5 1599.52      50 1595.37    66.8 1591.99
    87.5 1588.37    99.6 1586.63     110 1585.36   130.3 1583.72   143.3  1583.2
   151.8 1583.31   156.3 1582.73   160.8 1580.76   164.9 1579.72   169.3 1579.89
  171.38 1580.74   177.9 1583.69   203.9 1583.57   221.3 1586.73   248.4 1590.08
   256.7 1591.57   276.8 1596.72   310.5 1608.63   322.5 1611.76   341.6  1618.6
#Mann= 5 ,-1,0
       0      .1       0      20     .06       0      50      .1       0
   160.8    .045       0  171.38      .1       0
Bank Sta=160.8,171.38
XS Rating Curve= 0 ,0
Exp/Cntr(USF)=0,0
Exp/Cntr=0.3,0.1

Type RM Length L Ch R = 1 ,10772   ,177.2,177.7,175.7
XS GIS Cut Line= 6
2148653.71063193658694.1955350942148562.83777132658640.925237491
2148500.16683296658622.1239559842148485.75251714658614.603443381
2148412.42751926658588.2816492722148359.15722166658558.199598861
#Sta/Elev= 30
       0 1605.21     4.8  1604.8    41.6 1599.18    57.4 1596.12    66.7 1595.05
    85.2 1591.72   116.5 1589.08   124.8 1587.55     129 1586.37   137.3 1582.59
   141.5 1582.11   166.6 1582.86   170.8 1581.74   174.4 1580.14   179.8 1579.26
   184.3 1580.15   188.7 1581.06   197.2 1581.89     205 1583.47     210 1583.89
   222.7 1584.05   236.3 1582.91   239.7 1582.93   243.9 1583.63   253.6 1586.23
   260.9 1588.62   273.3 1593.23   282.1 1596.95     302 1603.79   326.1 1613.04
#Mann= 3 ,-1,0
       0      .1       0   174.4    .045       0   184.3      .1       0
Bank Sta=174.4,184.3
XS Rating Curve= 0 ,0
Exp/Cntr(USF)=0,0
Exp/Cntr=0.3,0.1

Type RM Length L Ch R = 1 ,10595   ,129.7,137.4,141
XS GIS Cut Line= 4
2148738.20698955658609.9610762862148605.25748763658502.596358241
2148475.96295483658446.8580790862148417.62287414658427.758747358
#Sta/Elev= 30
       0 1600.53    21.9 1596.32    52.2 1592.27    64.6 1590.98   149.9 1585.63
   170.9 1585.02   189.5 1582.99   215.6 1583.11   228.7 1582.56     233 1581.88
   237.4 1579.55   239.2 1579.03   241.8 1578.41   246.8 1578.89   254.8 1581.76
   259.2 1582.07   276.3 1580.84   285.3 1581.94     294 1580.97   298.4 1581.29
   303.7 1583.28   308.1 1585.54   315.7  1590.1   328.3 1598.56   332.5 1600.54
   341.4 1603.23   357.8 1612.02   366.2 1617.21   370.4 1619.33   373.1 1620.05
#Mann= 3 ,-1,0
       0      .1       0   239.2    .045       0   246.8      .1       0
Bank Sta=239.2,246.8
XS Rating Curve= 0 ,0
Exp/Cntr(USF)=0,0
Exp/Cntr=0.3,0.1

Type RM Length L Ch R = 1 ,10458   ,595.1,619.2,628.7
XS GIS Cut Line= 4
2148790.46373458658595.7135642152148693.58596146658507.070096888
2148502.14139305658308.5534091062148336.85229491658196.550686044
#Sta/Elev= 30
       0 1604.28     8.5 1600.54    27.5 1595.93    45.9 1592.21    62.9 1590.39
     128 1586.09   167.3 1585.17   200.6 1582.42   300.6 1581.94   306.2 1581.63
   314.7 1579.44   322.9 1578.22   328.4  1579.5     334 1581.32   346.5 1581.04
   352.3 1582.65   378.4 1601.43   396.7  1611.9   409.5 1618.11   454.2 1646.96
   470.2 1658.32   484.4 1663.79   510.9 1678.78   525.4 1683.04   535.1 1686.79
   549.2 1693.84   564.1 1695.05   573.8 1700.23   583.8 1703.17   606.8 1712.01
#Mann= 4 ,-1,0
       0     .06       0      50      .1       0   314.7    .045       0
   328.4      .1       0
Bank Sta=314.7,328.4
XS Rating Curve= 0 ,0
Exp/Cntr(USF)=0,0
Exp/Cntr=0.3,0.1

Type RM Length L Ch R = 1 ,9838    ,294.9,295.6,292.2
XS GIS Cut Line= 4
2148883.04276111658585.8725693542148874.30942426658469.414360767
2149022.88752803658217.9662542862149178.69393207658028.609763046
#Sta/Elev= 30
       0 1612.96     4.7 1611.05    12.7 1606.17    28.8 1605.09    40.6 1599.77
    56.9  1594.6      93 1587.07     113 1584.73   136.2  1583.7   172.8 1578.33
   205.3 1579.25   211.8 1577.43   222.7 1576.51   226.4  1577.3   232.2 1579.55
   238.4 1580.18   299.4 1579.18   330.8 1580.07   372.6 1578.49   387.8 1579.46
   391.2 1580.83   410.3 1592.97   446.1 1610.25   466.8 1619.46   492.7 1627.78
   513.5 1636.63   606.4  1688.6   618.6 1694.68     632 1700.17   654.1 1706.61
#Mann= 5 ,-1,0
       0     .06       0      70     .05       0   211.8    .045       0
   226.4     .05       0  286.79      .1       0
Bank Sta=211.8,226.4
XS Rating Curve= 0 ,0
Exp/Cntr(USF)=0,0
Exp/Cntr=0.3,0.1

Type RM Length L Ch R = 1 ,9542    ,272.5,275.2,273.5
XS GIS Cut Line= 4
2149073.78870029658594.3421914852149080.66616952658469.688061696
2149129.66813778658303.7691165282149162.33611663658197.168343467
#Sta/Elev= 30
       0 1619.62    17.2 1618.61    25.2 1617.02    29.2 1614.68    37.2  1608.7
    41.2  1607.1    53.2 1606.25    65.3 1600.29    73.3 1597.49    85.3 1594.21
   129.5 1586.77   154.6 1581.39   167.1 1580.44   174.2 1577.45   179.6 1575.94
   183.8 1576.46  186.211577.324   192.1 1578.82   196.3 1578.62   211.8 1579.41
   279.7 1578.35   283.9 1579.64   295.5 1586.06   300.6 1588.09   321.5 1593.73
   342.4 1601.02   350.8  1604.8     361 1610.35   375.6  1616.5   409.3 1632.49
#Mann= 5 ,-1,0
       0      .1       0      80     .06       0   174.2    .045       0
  186.21     .05       0  274.84      .1       0
Bank Sta=174.2,186.21
XS Rating Curve= 0 ,0
Exp/Cntr(USF)=0,0
Exp/Cntr=0.3,0.1

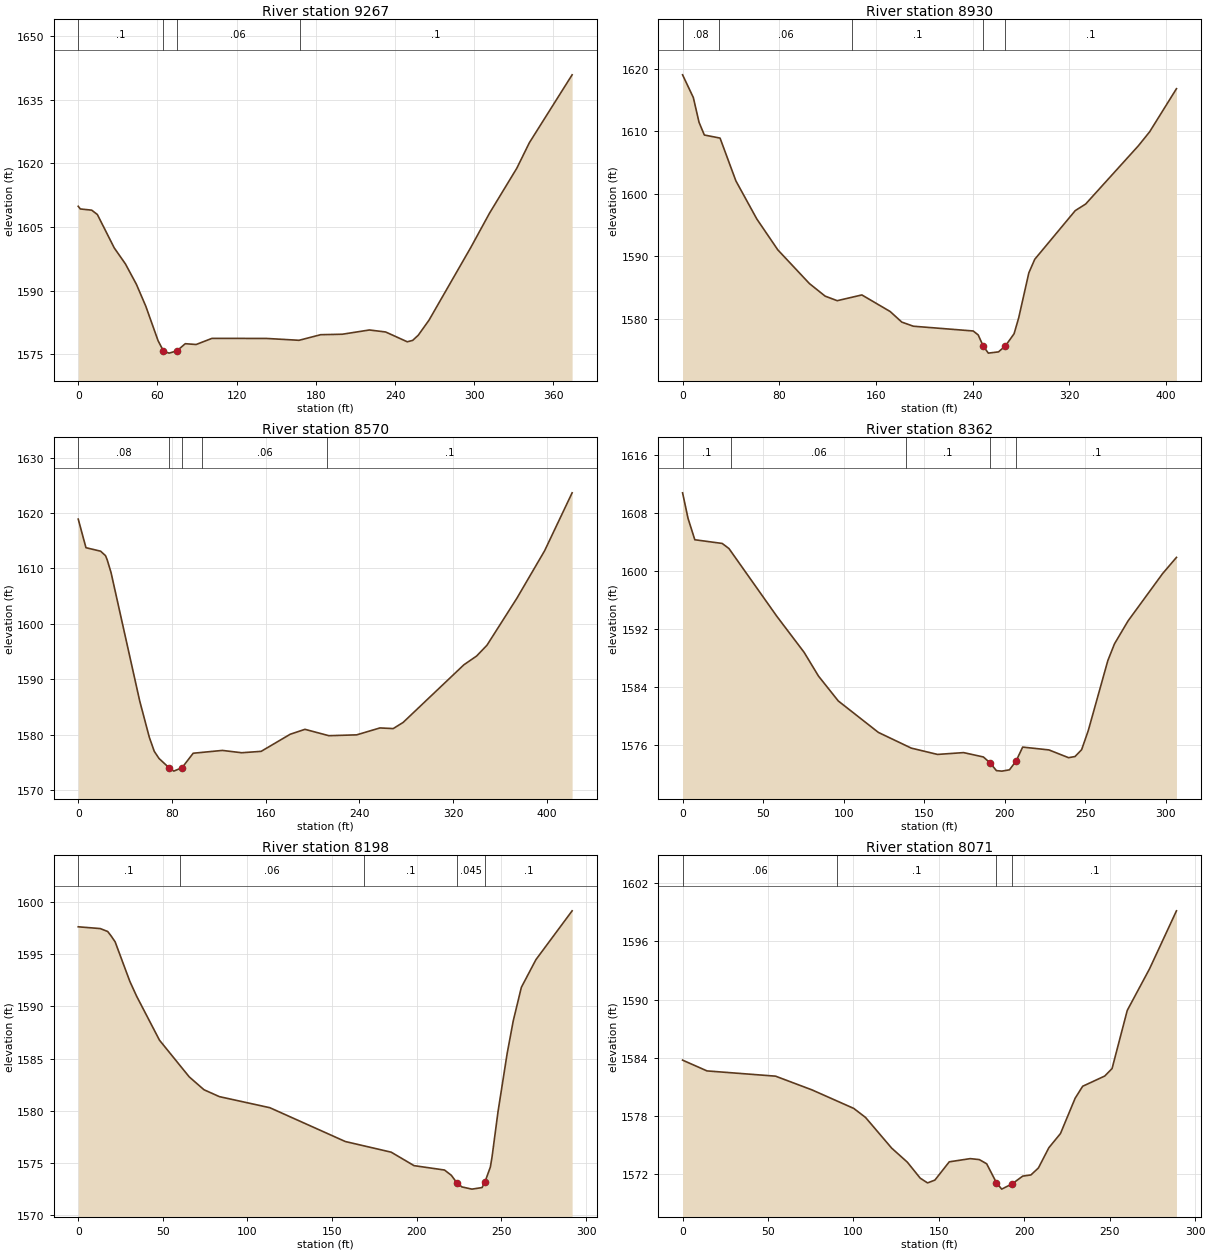
Type RM Length L Ch R = 1 ,9267    ,329.6,337.3,340.2
XS GIS Cut Line= 4
2149224.87864524658586.7029874982149238.25150208 658551.36043729
2149292.69813348658314.4698304882149321.35425527658225.635852937
#Sta/Elev= 30
       0 1609.86     1.6 1609.23    10.2 1608.95    14.5 1607.92    27.3 1600.05
    35.8 1596.27    44.1 1591.47    51.2 1586.32    60.5  1578.2    64.6 1575.78
    68.8 1575.28   74.721575.801    81.1  1577.5    89.3 1577.31   101.3 1578.75
   142.6 1578.74   167.3  1578.3   183.7 1579.62   200.1 1579.73   220.6 1580.73
   232.9 1580.26   249.3 1577.95   253.4 1578.28   257.6 1579.49   265.8 1583.06
   297.4 1600.15   311.6 1608.23   332.3 1618.83   341.8 1624.83   374.2 1640.82
#Mann= 4 ,-1,0
       0      .1       0    64.6    .045       0   74.72     .06       0
  167.79      .1       0
Bank Sta=64.6,74.72
XS Rating Curve= 0 ,0
Exp/Cntr(USF)=0,0
Exp/Cntr=0.3,0.1

Type RM Length L Ch R = 1 ,8930    ,352.8,359.4,358.9
XS GIS Cut Line= 4
2149369.11445826658649.746455438 2149427.3819059658512.197070843
2149468.45568046658377.513298427 2149510.7326627658266.989409048
#Sta/Elev= 30
       0    1619     8.9 1615.37    13.6 1611.43      18 1609.38      31 1608.89
    44.1 1602.05    61.4 1595.96    78.8 1591.02   104.9 1585.64   117.9 1583.63
   127.9  1582.9   148.3 1583.82   171.7 1581.17   181.3 1579.48   190.9 1578.82
   240.4 1578.06   244.5 1577.43   248.7 1575.64   252.9 1574.52   261.3 1574.72
     267 1575.67   274.2 1577.62     278 1580.15   286.4 1587.35   291.3 1589.52
   324.8  1597.3   333.4 1598.35     377 1607.66   386.3 1609.89   408.5 1616.78
#Mann= 5 ,-1,0
       0     .08       0      30     .06       0     140      .1       0
   248.7    .045       0     267      .1       0
Bank Sta=248.7,267
XS Rating Curve= 0 ,0
Exp/Cntr(USF)=0,0
Exp/Cntr=0.3,0.1

Type RM Length L Ch R = 1 ,8570    ,207.5,208.4,209.1
XS GIS Cut Line= 5
2149551.55843366658719.4763517952149562.06567831658685.089005646
2149606.00506506658524.6147236192149693.88383855658451.064011023
2149754.78921891 658366.12208738
#Sta/Elev= 30
       0  1618.9     6.6 1613.74    19.1 1613.11    23.3  1612.3    24.8  1611.5
      28 1609.25    52.5 1586.03    60.7 1579.48    64.9 1576.96      69 1575.66
    77.3 1574.04    81.5 1573.39    88.61574.007    98.1 1576.62     123 1577.13
   139.5 1576.71   156.1 1576.96     181 1580.06   193.5 1580.94   213.9 1579.79
   237.6 1579.94   257.5 1581.19   268.8 1581.07   277.3 1582.19   329.1 1592.59
     340 1594.18   348.8 1596.12   374.4 1604.63     398 1613.18   421.5 1623.65
#Mann= 5 ,-1,0
       0     .08       0    77.3    .045       0    88.6     .08       0
  105.96     .06       0  212.34      .1       0
Bank Sta=77.3,88.6
XS Rating Curve= 0 ,0
Exp/Cntr(USF)=0,0
Exp/Cntr=0.3,0.1

Type RM Length L Ch R = 1 ,8362    ,160.2,163.6,166
XS GIS Cut Line= 5
2149704.03899421658748.3595317312149740.38813846658645.579192828
2149767.33664195658502.0627439922149764.20309503658486.395009403
2149777.36399209658453.179412075
#Sta/Elev= 30
       0 1610.78     3.4 1607.26     7.6 1604.32    24.6 1603.81    28.8 1603.11
    58.5 1593.79    75.5 1588.81    84.4 1585.55    96.7 1582.12   121.6 1577.79
     142 1575.63   158.3 1574.76   174.5 1575.01   186.8 1574.41   190.8 1573.63
   194.9 1572.53   198.3 1572.46     203 1572.64   207.1 1573.85   211.2 1575.77
   227.5 1575.38   239.7 1574.31   243.7 1574.47   247.8 1575.41   251.9 1578.02
   264.1 1587.69   268.2 1589.98   276.6 1593.13   298.1 1599.66   306.7 1601.89
#Mann= 5 ,-1,0
       0      .1       0      30     .06       0  139.02      .1       0
   190.8    .045       0   207.1      .1       0
Bank Sta=190.8,207.1
XS Rating Curve= 0 ,0
Exp/Cntr(USF)=0,0
Exp/Cntr=0.3,0.1

Type RM Length L Ch R = 1 ,8198    ,128.4,127.5,127.6
XS GIS Cut Line= 4
2149802.43236743658769.0409413892149863.22317764658633.045005156
2149912.73321894658537.7851788552149931.53450044658507.703128444
#Sta/Elev= 30
       0 1597.63      13 1597.46    17.4 1597.18    19.4 1596.76    21.8 1596.19
    30.5  1592.4    34.5 1590.98      48 1586.77    65.6 1583.25    74.3 1582.02
    83.4 1581.36   113.2  1580.3   157.8 1577.06   184.9 1576.04   198.4 1574.75
   216.4 1574.33   220.4 1573.83   223.7 1573.11   226.7 1572.71   232.6  1572.5
   238.6 1572.65   240.3 1573.19   243.5 1574.62   244.5  1575.6     248  1579.9
   253.4 1585.48     257 1588.61   261.8 1591.83   270.4 1594.48   291.8 1599.16
#Mann= 5 ,-1,0
       0      .1       0      60     .06       0  168.96      .1       0
   223.7    .045       0   240.3      .1       0
Bank Sta=223.7,240.3
XS Rating Curve= 0 ,0
Exp/Cntr(USF)=0,0
Exp/Cntr=0.3,0.1

Type RM Length L Ch R = 1 ,8071    ,102.1,100.2,98.9
XS GIS Cut Line= 5
2149966.41323134658807.4584630172149963.83418038658743.841872642
2149971.57133326658718.0513630312150033.46855633658566.747039976
2150048.08317844658534.938744789
#Sta/Elev= 30
       0 1583.77    14.3 1582.66    54.4 1582.12    75.7 1580.71   100.2  1578.8
   107.1 1577.87   122.4 1574.71   131.6 1573.26   139.1 1571.62   143.4 1571.13
   147.7 1571.42   156.1  1573.3   168.4 1573.63   173.7 1573.53     178  1573.1
   183.7 1571.16   186.8 1570.49   192.9 1571.03   199.1 1571.83   203.9 1571.95
   208.3 1572.67   214.4 1574.75   221.2 1576.21   229.8 1579.85   234.2 1581.08
   247.1 1582.13   251.4  1582.9   260.3 1588.89   273.4 1593.19   289.1 1599.14
#Mann= 4 ,-1,0
       0     .06       0   90.59      .1       0   183.7    .045       0
   192.9      .1       0
Bank Sta=183.7,192.9
XS Rating Curve= 0 ,0
Exp/Cntr(USF)=0,0
Exp/Cntr=0.3,0.1

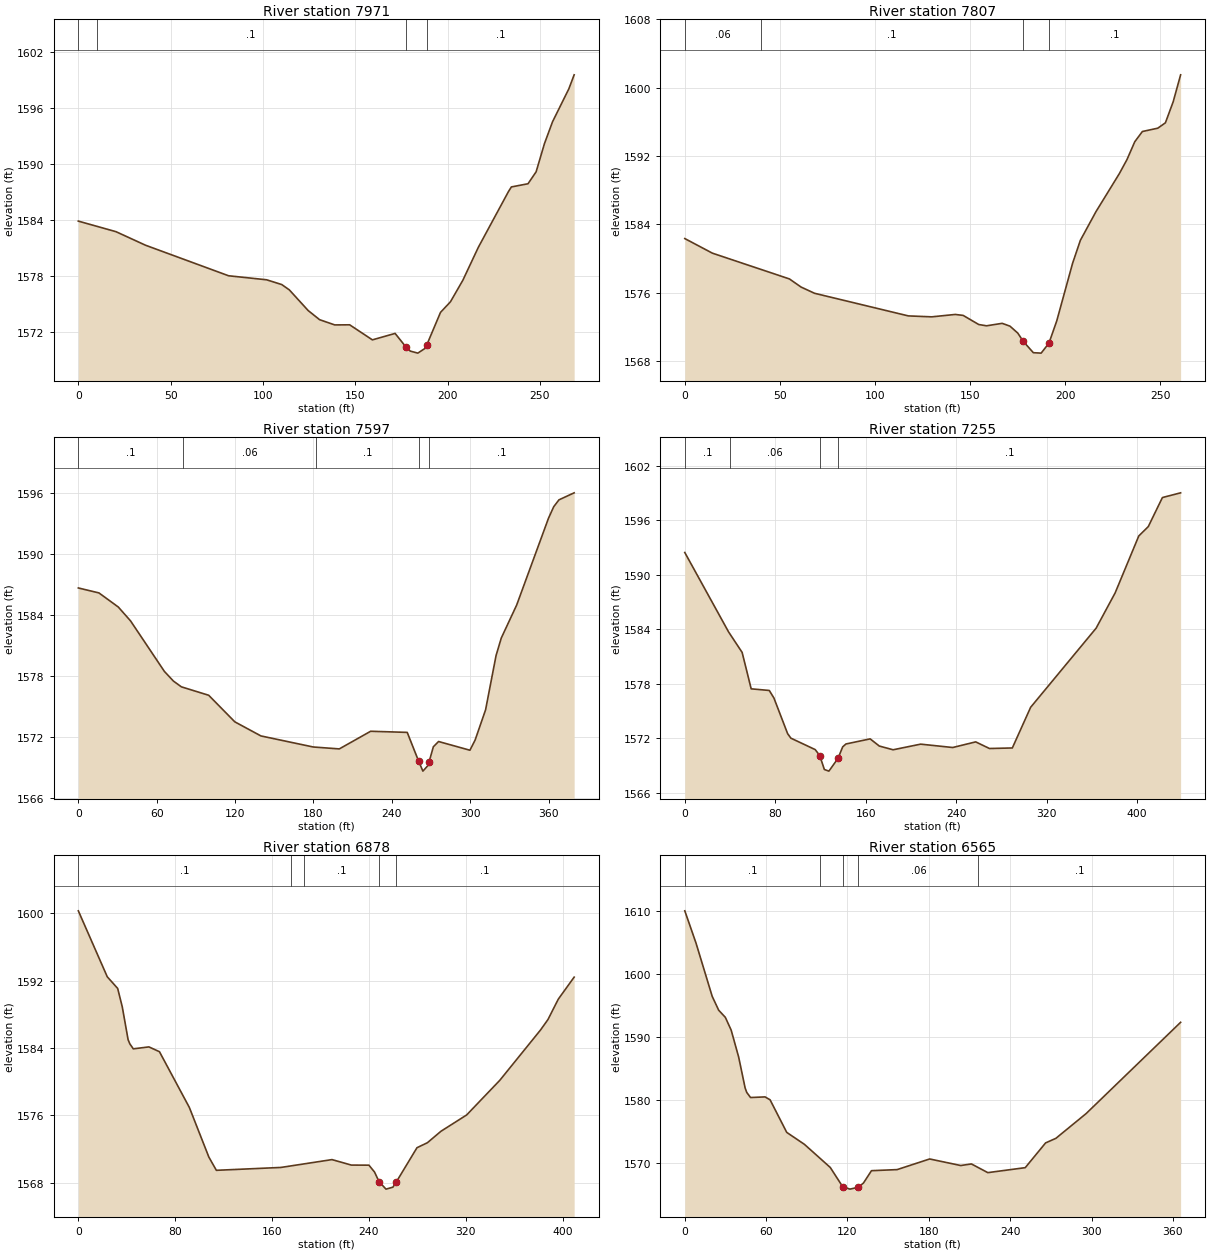
Type RM Length L Ch R = 1 ,7971    ,164,164.2,164.3
XS GIS Cut Line= 5
 2150073.0140044658825.5118197462150076.45273901658779.088902445
2150089.34799382658724.9288322612150114.27881978658613.169957277
2150137.49027843658566.747039976
#Sta/Elev= 30
       0 1583.86    20.4 1582.73    36.4 1581.28    81.4 1578.01     102 1577.58
   110.2 1577.07   114.3  1576.5   124.5 1574.29   130.7 1573.31   138.9 1572.75
     147 1572.76   159.3 1571.15   171.6 1571.84   177.3 1570.43   179.8 1569.95
   183.9 1569.73     188 1570.26   188.7 1570.58   196.2 1574.09   201.6 1575.23
   208.3 1577.53   216.7 1581.06     233 1587.02   234.6 1587.52   243.6 1587.86
     248 1589.14   252.5 1592.15   256.9  1594.5   265.7 1598.01   268.6 1599.52
#Mann= 4 ,-1,0
       0     .06       0      10      .1       0   177.3    .045       0
   188.7      .1       0
Bank Sta=177.3,188.7
XS Rating Curve= 0 ,0
Exp/Cntr(USF)=0,0
Exp/Cntr=0.3,0.1

Type RM Length L Ch R = 1 ,7807    ,211.5,210,207.1
XS GIS Cut Line= 4
2150198.08937918658844.8031209352150238.47731723658803.022495364
  2150276.776224 658638.685368122150281.65063032658605.260867663
#Sta/Elev= 30
       0 1582.32    14.5 1580.61      55 1577.59    61.1 1576.64    68.2 1575.91
   117.5 1573.26   129.8 1573.15   142.1 1573.43   146.3 1573.32   154.5 1572.25
   158.6  1572.1   166.8 1572.39   170.9 1572.06     175 1571.25   177.91570.274
   183.2 1568.95   187.3  1568.9   191.4 1570.07   195.5 1572.68   203.8 1579.41
   207.9 1582.11   216.1 1585.47   228.4 1589.93   232.4 1591.57   236.5 1593.66
   240.5 1594.86   248.6 1595.25   252.6 1595.88   256.7 1598.35   260.6  1601.5
#Mann= 4 ,-1,0
       0     .06       0      40      .1       0   177.9    .045       0
   191.4      .1       0
Bank Sta=177.9,191.4
XS Rating Curve= 0 ,0
Exp/Cntr(USF)=0,0
Exp/Cntr=0.3,0.1

Type RM Length L Ch R = 1 ,7597    ,338.7,342.1,341.1
XS GIS Cut Line= 4
2150428.57916358658986.1609041162150463.39635155658901.206965456
2150463.39635155658670.0208372982150468.27075787658613.616992777
#Sta/Elev= 30
       0 1586.67    15.8 1586.18    30.6 1584.79      40 1583.42    65.9 1578.44
    72.8 1577.49    78.9 1576.92    99.8 1576.09   119.8 1573.47   139.8 1572.08
   179.8 1570.99   199.8  1570.8   223.8 1572.54   251.8 1572.43   260.6 1569.57
   263.8 1568.61   267.8 1569.18   268.6 1569.55   271.8 1571.01   275.8 1571.53
   299.8 1570.67   303.8 1571.68   311.8 1574.66   319.8    1580   323.8 1581.73
   335.6 1584.99     360 1593.56     364 1594.69     368 1595.36   379.6 1596.05
#Mann= 5 ,-1,0
       0      .1       0      80     .06       0  181.81      .1       0
   260.6    .045       0   268.6      .1       0
Bank Sta=260.6,268.6
XS Rating Curve= 0 ,0
Exp/Cntr(USF)=0,0
Exp/Cntr=0.3,0.1

Type RM Length L Ch R = 1 ,7255    ,365.3,376.7,376.9
XS GIS Cut Line= 4
2150702.85241294658947.8944160142150702.22570356658872.689289986
2150744.21523226658621.3788271782150712.12793258658517.857430351
#Sta/Elev= 30
       0 1592.47    38.7 1583.73    50.7 1581.47    58.7 1577.46    74.7 1577.28
    78.8 1576.45    90.9 1572.53    93.8 1572.03   115.3 1570.77   119.3 1570.12
   123.4 1568.58   127.4  1568.4   135.5 1569.81   139.6 1571.07   142.5 1571.39
   163.9 1571.95     172 1571.16   184.2 1570.75   208.5 1571.37   236.9    1571
   257.2 1571.62   269.4 1570.89   289.6 1570.95   305.8 1575.43   363.7 1584.14
   380.5 1588.02   401.4 1594.29   409.8 1595.32   422.3 1598.52   438.4 1599.04
#Mann= 4 ,-1,0
       0      .1       0      40     .06       0   119.3    .045       0
   135.5      .1       0
Bank Sta=119.3,135.5
XS Rating Curve= 0 ,0
Exp/Cntr(USF)=0,0
Exp/Cntr=0.3,0.1

Type RM Length L Ch R = 1 ,6878    ,310.3,313.2,312.3
XS GIS Cut Line= 4
2150839.18356854658975.3869409762150870.99186373 658895.43636118
2151001.66377909658723.499630436 2151085.0530935658655.584621793
#Sta/Elev= 30
       0 1600.26    23.9 1592.44    32.5 1591.06    36.3 1588.87    41.1 1584.99
    42.5  1584.5    45.4  1583.9    58.3 1584.13      67 1583.56    91.7 1576.95
   107.8 1571.07     114  1569.5   167.3 1569.84   209.5 1570.77   225.5 1570.12
     240 1570.11   244.6  1569.3   248.4 1568.15   254.1 1567.27   259.8  1567.5
  262.561568.108   279.7 1572.18   288.3 1572.77   299.5 1574.13   320.7 1576.06
   348.1 1580.17   381.7 1586.13   387.9 1587.38   396.4 1589.79   409.5  1592.4
#Mann= 5 ,-1,0
       0      .1       0  176.05     .06       0  186.05      .1       0
   248.4    .045       0  262.56      .1       0
Bank Sta=248.4,262.56
XS Rating Curve= 0 ,0
Exp/Cntr(USF)=0,0
Exp/Cntr=0.3,0.1

Type RM Length L Ch R = 1 ,6565    ,312.2,320.4,323.9
XS GIS Cut Line= 5
2151041.14240219 659093.712352512151086.70563584659028.376394827
 2151106.7465239658997.4744020562151201.64529468658869.048672465
2151249.27520783658793.216837054
#Sta/Elev= 30
       0    1610     8.3 1604.86    20.2 1596.42      25 1594.21    29.9 1593.08
    34.2 1591.05    39.7  1586.8    44.5 1581.86    45.7 1581.15    48.5 1580.34
    59.2 1580.44    62.9 1579.98    75.2  1574.8    88.2 1572.91   107.3 1569.23
   116.5 1566.16   121.8 1565.79     1281566.086   131.8 1566.77   137.7 1568.72
   156.6 1568.89   180.6 1570.58   203.5 1569.54   211.4 1569.79   223.5 1568.41
   251.1  1569.2   266.1 1573.13   273.7 1573.86     296 1577.79   365.7 1592.29
#Mann= 5 ,-1,0
       0      .1       0   99.65     .06       0   116.5    .045       0
     128     .06       0  216.49      .1       0
Bank Sta=116.5,128
XS Rating Curve= 0 ,0
Exp/Cntr(USF)=0,0
Exp/Cntr=0.3,0.1