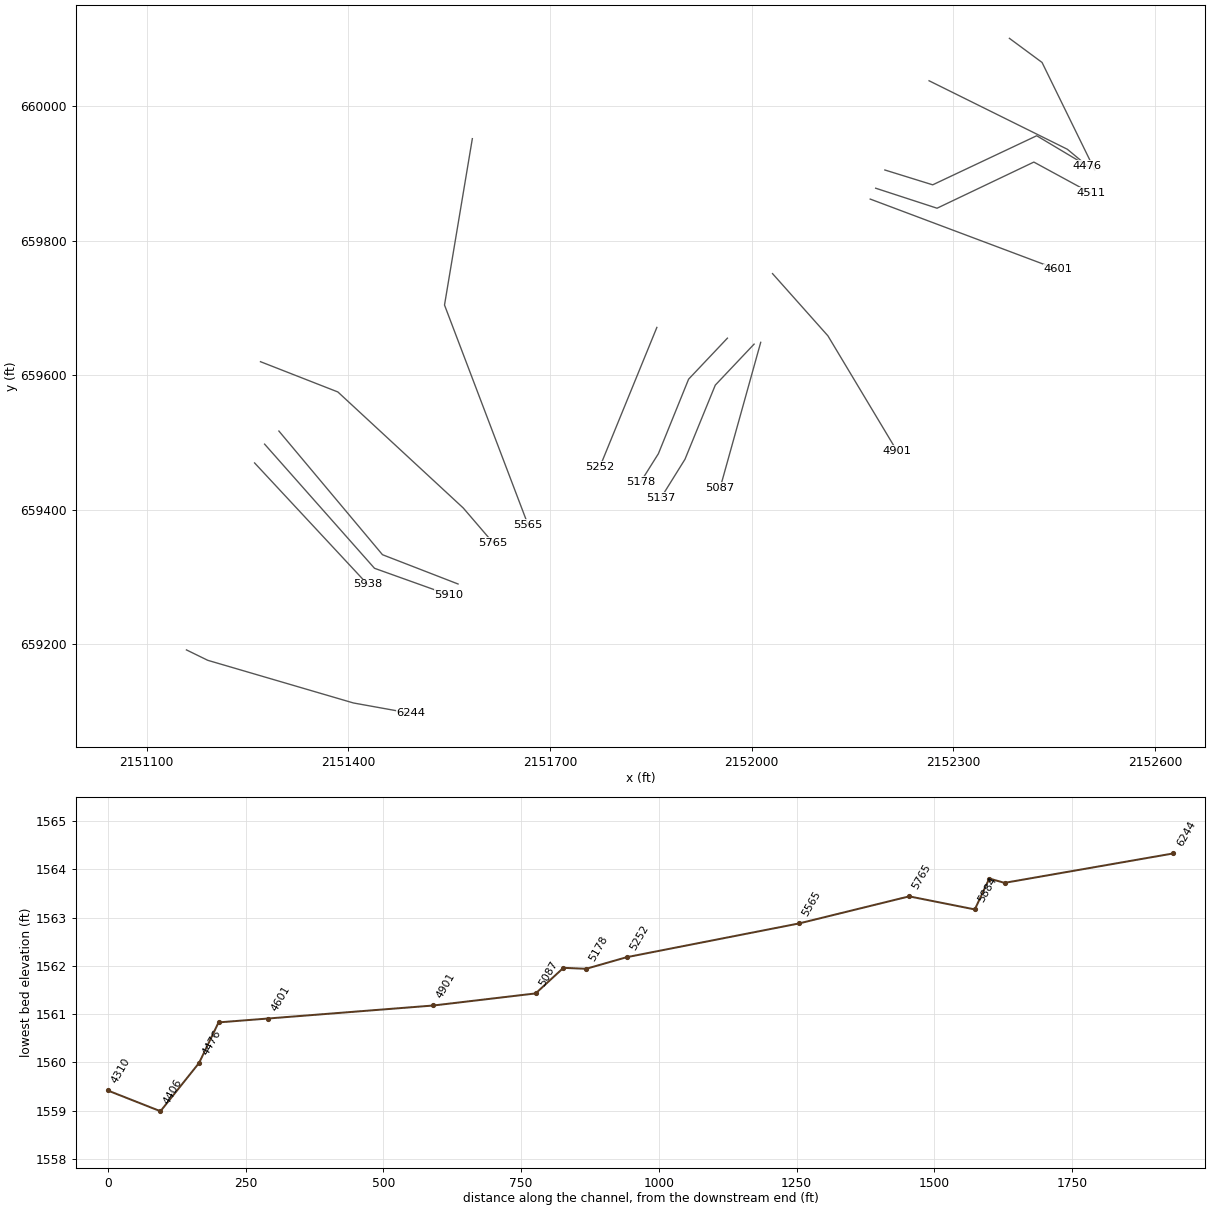
HEC-RAS study COWRN.prj: COWRN

--- COWRN.g01 (geometry) --- (continued)

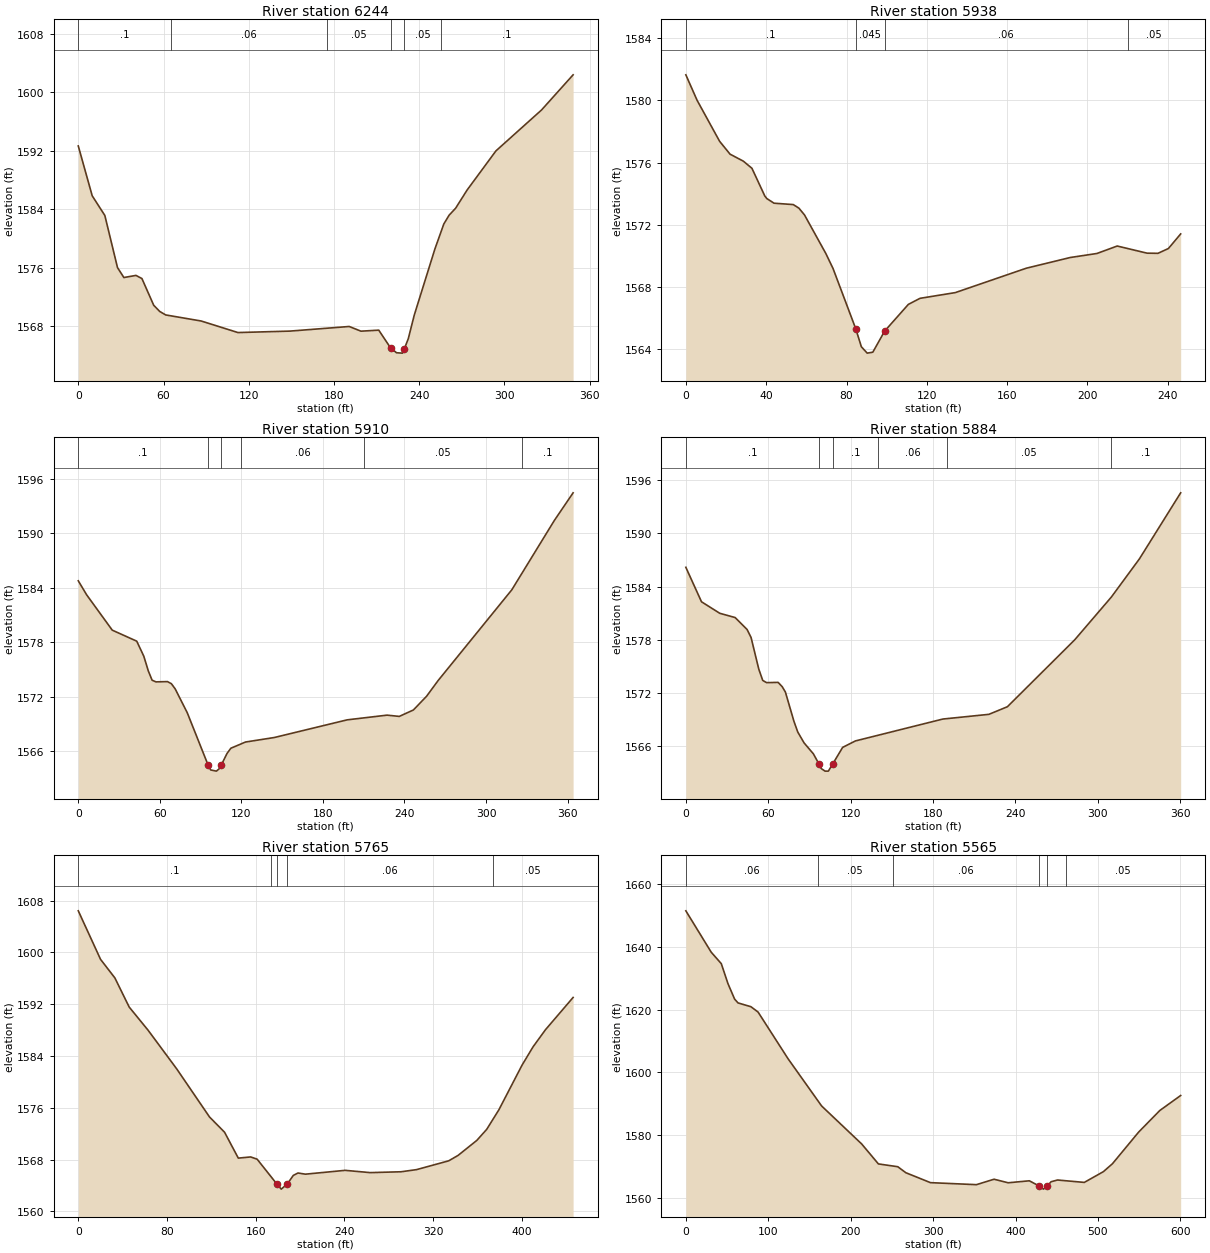
Type RM Length L Ch R = 1 ,6244    ,310,306.6,299
XS GIS Cut Line= 4
2151159.34872566659191.2247374182151191.07105249659175.750431651
2151407.71133322659112.3057780072151493.59373023 659096.83147224
#Sta/Elev= 30
       0 1592.64     9.8 1585.83    18.7 1583.14    27.6 1576.02    32.1 1574.66
    40.6 1574.95    44.8 1574.52    53.1 1570.87    57.3 1570.03    61.5 1569.55
    86.5 1568.72   112.4 1567.14     149 1567.34   190.7 1567.97     199 1567.33
   211.5 1567.47   219.8 1565.05     224 1564.38   228.2 1564.33   229.5 1564.91
   232.3 1566.31   236.5 1569.53     251 1578.55   257.3 1581.98     261 1583.17
   265.6 1584.13   273.7 1586.62     294 1591.97   326.1 1597.56   348.3 1602.36
#Mann= 6 ,-1,0
       0      .1       0    65.3     .06       0   175.3     .05       0
   219.8    .045       0   229.5     .05       0   255.3      .1       0
Bank Sta=219.8,229.5
XS Rating Curve= 0 ,0
Exp/Cntr(USF)=0,0
Exp/Cntr=0.3,0.1

Type RM Length L Ch R = 1 ,5938    ,27.8,27.6,27.4
XS GIS Cut Line= 2
2151260.71046732659469.283578488 2151428.6329838659288.898062742
#Sta/Elev= 30
       0 1581.65     5.6 1580.01    16.8 1577.37      22 1576.54    28.6 1576.09
    32.9 1575.63    39.3 1573.85    40.3 1573.68    43.9 1573.38    53.5 1573.29
    56.3 1573.06    59.1 1572.62    69.7 1570.14    73.3 1569.17    84.6 1565.29
    87.4 1564.13    90.3 1563.72    93.1 1563.78      99 1565.14   110.8 1566.86
   116.6 1567.25   134.2 1567.62   169.5 1569.19   191.4 1569.88   204.7 1570.14
   214.8 1570.62   229.7 1570.16   235.1 1570.15   240.3 1570.46   246.4  1571.4
#Mann= 4 ,-1,0
       0      .1       0    84.6    .045       0      99     .06       0
     220     .05       0
Bank Sta=84.6,99
XS Rating Curve= 0 ,0
Exp/Cntr(USF)=0,0
Exp/Cntr=0.3,0.1

Type RM Length L Ch R = 1 ,5910    ,26.4,26.3,25.9
XS GIS Cut Line= 3
2151275.58924184 659497.254994632151439.02892174659312.613412264
2151549.69326469 659273.01791341
#Sta/Elev= 30
       0 1584.75     6.1 1583.22      25 1579.32      43 1578.11    48.2 1576.46
    51.5 1574.85    54.3 1573.82    57.1 1573.63    65.6 1573.66    68.5 1573.43
    71.3 1572.86    80.2 1570.23   95.521564.477    97.4 1563.94   101.6 1563.81
   103.5 1564.04   105.3 1564.51   109.5 1565.77   112.3 1566.33     123 1567.01
   144.3 1567.51   197.8 1569.45   227.2 1569.97   236.2 1569.83   246.6 1570.54
   256.3 1572.05   264.8 1573.78     319 1583.76   350.3 1591.39   364.1 1594.43
#Mann= 6 ,-1,0
       0      .1       0   95.52    .045       0   105.3      .1       0
     120     .06       0     210     .05       0  326.59      .1       0
Bank Sta=95.52,105.3
XS Rating Curve= 0 ,0
Exp/Cntr(USF)=0,0
Exp/Cntr=0.3,0.1

Type RM Length L Ch R = 1 ,5884    ,117.7,119.2,120.3
XS GIS Cut Line= 3
2151296.86011917659516.7203795062151450.90874268659332.815527576
2151563.30361198659289.248803241
#Sta/Elev= 30
       0 1586.18    11.4 1582.29    24.7 1580.99    35.9 1580.51    44.6 1579.16
    47.5 1578.26    53.1  1574.7      56 1573.41    58.8 1573.16    67.2 1573.19
    70.2  1572.7    72.5  1572.1    78.7 1568.81    81.5 1567.59    86.1 1566.36
    92.9 1565.12   97.131563.921    98.6 1563.46   101.4 1563.17   103.8 1563.17
   107.1 1564.01   114.2 1565.85   123.5 1566.58   187.2 1569.05   220.7 1569.58
   234.2 1570.44   283.2 1577.99   309.9 1582.82   330.3 1587.12   360.4 1594.59
#Mann= 6 ,-1,0
       0      .1       0   97.13    .045       0   107.1      .1       0
     140     .06       0     190     .05       0   309.9      .1       0
Bank Sta=97.13,107.1
XS Rating Curve= 0 ,0
Exp/Cntr(USF)=0,0
Exp/Cntr=0.3,0.1

Type RM Length L Ch R = 1 ,5765    ,202.8,199.6,194.1
XS GIS Cut Line= 4
2151269.46640399659619.8798695292151384.54690058 659574.85905642
2151571.01228508659402.320547118 2151615.6855217659350.279372703
#Sta/Elev= 30
       0 1606.42    20.1 1598.92      33 1596.06    45.9 1591.56      63 1587.97
    88.8    1582   118.4 1574.57   131.9 1572.23   144.3 1568.23   155.5 1568.41
   161.3 1568.06179.08441564.224     183 1563.44188.48441564.237   193.9 1565.56
   198.1 1565.93   204.8 1565.75   240.6 1566.34   263.2 1565.99     291 1566.12
     305 1566.45     334 1567.81   342.5 1568.65   359.4 1570.97   368.3 1572.67
   379.3  1575.7   400.2  1582.6   410.1 1585.42   421.3 1588.06   446.2 1593.04
#Mann= 5 ,-1,0
       0      .1       0  173.57     .06       0179.0844    .045       0
188.4844     .06       0  373.57     .05       0
Bank Sta=179.0844,188.4844
XS Rating Curve= 0 ,0
Exp/Cntr(USF)=0,0
Exp/Cntr=0.3,0.1

Type RM Length L Ch R = 1 ,5565    ,319.8,313.2,304.9
XS GIS Cut Line= 3
2151584.55319378659951.5857239352151543.16282728659704.143315504
2151667.33392678659377.519336374
#Sta/Elev= 30
       0 1651.42    30.8 1638.25      43 1634.61    51.1 1628.25    59.2 1623.32
    63.3 1622.12    78.9 1620.92    87.6 1619.22     124 1604.36   164.7 1589.34
   213.3 1577.25   233.6  1570.9   257.1 1570.01   266.9  1568.1   296.8 1564.94
   352.5  1564.3   373.9 1566.03     391  1564.9   416.7 1565.53   428.81563.854
   433.8 1562.88   438.51563.908   443.1 1565.23   450.9 1565.78   483.4 1565.02
   506.5 1568.43   517.5 1570.95   549.3 1581.02     575  1587.9   600.3 1592.67
#Mann= 6 ,-1,0
       0     .06       0     160     .05       0  250.88     .06       0
   428.8    .045       0   438.5     .06       0  460.88     .05       0
Bank Sta=428.8,438.5
XS Rating Curve= 0 ,0
Exp/Cntr(USF)=0,0
Exp/Cntr=0.3,0.1

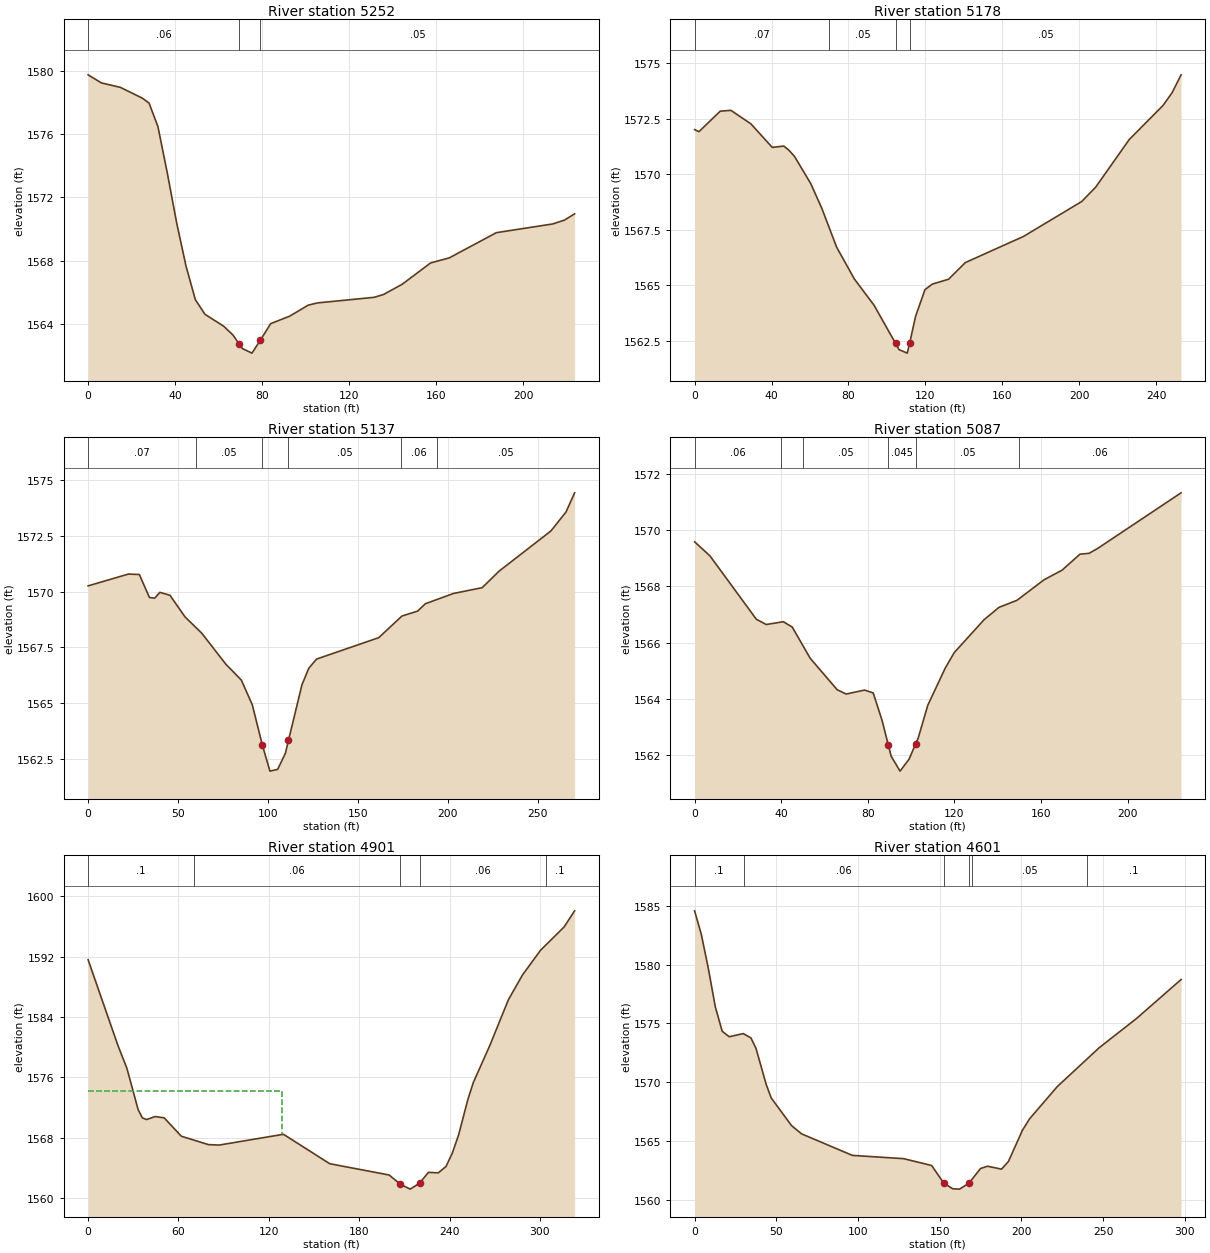
Type RM Length L Ch R = 1 ,5252    ,73.6,73.4,73.3
XS GIS Cut Line= 2
2151858.98931949659670.8510641872151774.40900534659463.899231681
#Sta/Elev= 30
       0 1579.74     6.1 1579.23    14.8 1578.95    24.9 1578.27      28 1577.96
    32.1 1576.47    36.4 1573.54    40.7  1570.4      45 1567.67    49.3 1565.55
    53.7 1564.63    62.3 1563.88    66.6 1563.32    69.31562.786    70.9 1562.47
    75.3 1562.18    79.11562.979    83.9 1564.04    92.6 1564.51   101.2 1565.21
   105.5 1565.35   131.4  1565.7   135.8 1565.88   144.4 1566.53   157.4 1567.87
     166 1568.19   187.6 1569.78   213.5 1570.33   218.9 1570.57   223.6 1570.97
#Mann= 3 ,-1,0
       0     .06       0    69.3    .045       0    79.1     .05       0
Bank Sta=69.3,79.1
XS Rating Curve= 0 ,0
Exp/Cntr(USF)=0,0
Exp/Cntr=0.3,0.1

Type RM Length L Ch R = 1 ,5178    ,42,41.2,41.1
XS GIS Cut Line= 4
2151963.91254889659654.8712334512151906.18918385659593.868131762
2151861.26646116659483.0433224622151834.95330381659441.163593341
#Sta/Elev= 30
       0 1572.01     2.3 1571.92    13.3 1572.84    18.9 1572.88    29.3 1572.27
    40.4 1571.21    46.4 1571.27    49.1 1571.08      52  1570.8    60.4 1569.58
    66.1 1568.48    73.9 1566.71    83.1 1565.28    93.4 1564.09104.52161562.377
   106.3  1562.1   110.6 1561.94111.89341562.411   114.9 1563.59   119.8  1564.8
   123.6 1565.05   132.1 1565.27   140.8 1566.02   171.1  1567.2   201.3 1568.77
   208.6 1569.42     226 1571.56   243.6  1573.1   248.3 1573.67     253 1574.48
#Mann= 4 ,-1,0
       0     .07       0      70     .05       0104.5216    .045       0
111.8934     .05       0
Bank Sta=104.5216,111.8934
XS Rating Curve= 0 ,0
Exp/Cntr(USF)=0,0
Exp/Cntr=0.3,0.1

Type RM Length L Ch R = 1 ,5137    ,49.2,50.5,51.6
XS GIS Cut Line= 4
2152003.59736235659646.0159444962151945.87399731659585.012842807
2151900.82008516659474.7783861042151865.19247572659417.549489461
#Sta/Elev= 30
       0 1570.26    22.4 1570.79    28.5 1570.77    34.1 1569.74      37 1569.71
    39.9 1569.97    45.5 1569.84    53.9 1568.87    63.2 1568.14    76.6 1566.75
    85.2 1566.04    91.3 1564.93    96.8 1563.15   101.1 1561.96   105.4 1562.04
   109.7 1562.76  111.411563.339   118.9 1565.83   122.7 1566.57     127 1566.98
   161.6 1567.94   174.5 1568.91   183.2 1569.13   187.5 1569.46   203.1 1569.92
   219.1 1570.18   228.5 1570.92   257.3 1572.72   265.7 1573.57   270.5 1574.43
#Mann= 6 ,-1,0
       0     .07       0      60     .05       0    96.8    .045       0
  111.41     .05       0  173.98     .06       0  193.98     .05       0
Bank Sta=96.8,111.41
XS Rating Curve= 0 ,0
Exp/Cntr(USF)=0,0
Exp/Cntr=0.3,0.1

Type RM Length L Ch R = 1 ,5087    ,177.4,185.5,193.7
XS GIS Cut Line= 2
 2152013.4365723659648.6397338162151953.08941794 659432.17711492
#Sta/Elev= 30
       0 1569.58     7.1 1569.08    28.5 1566.83    33.1 1566.64      41 1566.74
    45.1 1566.55    53.4 1565.44    65.9 1564.32      70 1564.17    78.5 1564.31
    82.5 1564.21    86.6 1563.23    89.5 1562.35    90.8 1561.96    94.9 1561.43
    99.1 1561.86   102.11562.396   103.3 1562.61   107.7 1563.77   115.7 1565.08
   119.9 1565.64   133.7 1566.81   140.6 1567.25   148.9  1567.5   161.4 1568.23
   169.7 1568.57     178 1569.14   182.2 1569.17   186.3 1569.35   224.7 1571.32
#Mann= 6 ,-1,0
       0     .06       0      40     .07       0      50     .05       0
    89.5    .045       0   102.1     .05       0     150     .06       0
Bank Sta=89.5,102.1
XS Rating Curve= 0 ,0
Exp/Cntr(USF)=0,0
Exp/Cntr=0.3,0.1

Type RM Length L Ch R = 1 ,4901    ,292.6,300.6,305.7
XS GIS Cut Line= 3
 2152031.0193253 659750.86403236 2152113.3689383659658.361727346
2152215.77325157659487.583420325
#Sta/Elev= 30
       0 1591.58    19.8 1580.22    25.8 1577.17    33.2 1571.72      36 1570.63
    38.8  1570.4    44.5  1570.8    50.5 1570.63    61.9 1568.19    79.9 1567.08
      87 1567.02   129.7 1568.45   160.4 1564.55   199.9 1563.05   207.1 1561.86
   213.8 1561.18   220.1 1561.97   225.9  1563.4   232.5 1563.34   237.6 1564.18
   241.8 1565.96     246 1568.37   252.1 1573.05   255.8 1575.34   266.7 1580.22
   279.1 1586.31   288.5  1589.6   300.4 1592.85     316 1595.93     323 1598.07
#Mann= 5 ,-1,0
       0      .1       0      70     .06       0   207.1    .045       0
   220.1     .06       0  303.85      .1       0
#XS Ineff= 2 , 0
          128.96 1574.24
Permanent Ineff=
       F       F
Bank Sta=207.1,220.1
XS Rating Curve= 0 ,0
Exp/Cntr(USF)=0,0
Exp/Cntr=0.3,0.1

Type RM Length L Ch R = 1 ,4601    ,82.1,89.3,95.3
XS GIS Cut Line= 2
2152176.30912294 659861.714006542152455.09132982659756.991359361
#Sta/Elev= 30
       0 1584.58     4.1 1582.59     8.4 1579.69    12.7 1576.41    16.9 1574.34
    21.2 1573.87    29.8 1574.14    34.5 1573.77    37.6 1572.88    43.8 1569.83
    46.9 1568.67    59.3 1566.32    65.5 1565.61    96.6 1563.78     128  1563.5
   145.1 1562.92   152.5 1561.43     158 1560.94   162.2 1560.91     168 1561.42
     175 1562.66   179.3 1562.86   187.9 1562.61   192.1 1563.26   200.7 1565.92
     205 1566.88     222 1569.63   247.7 1572.94   270.5 1575.42   297.8 1578.74
#Mann= 6 ,-1,0
       0      .1       0      30     .06       0   152.5    .045       0
     168     .06       0     170     .05       0     240      .1       0
Bank Sta=152.5,168
XS Rating Curve= 0 ,0
Exp/Cntr(USF)=0,0
Exp/Cntr=0.3,0.1

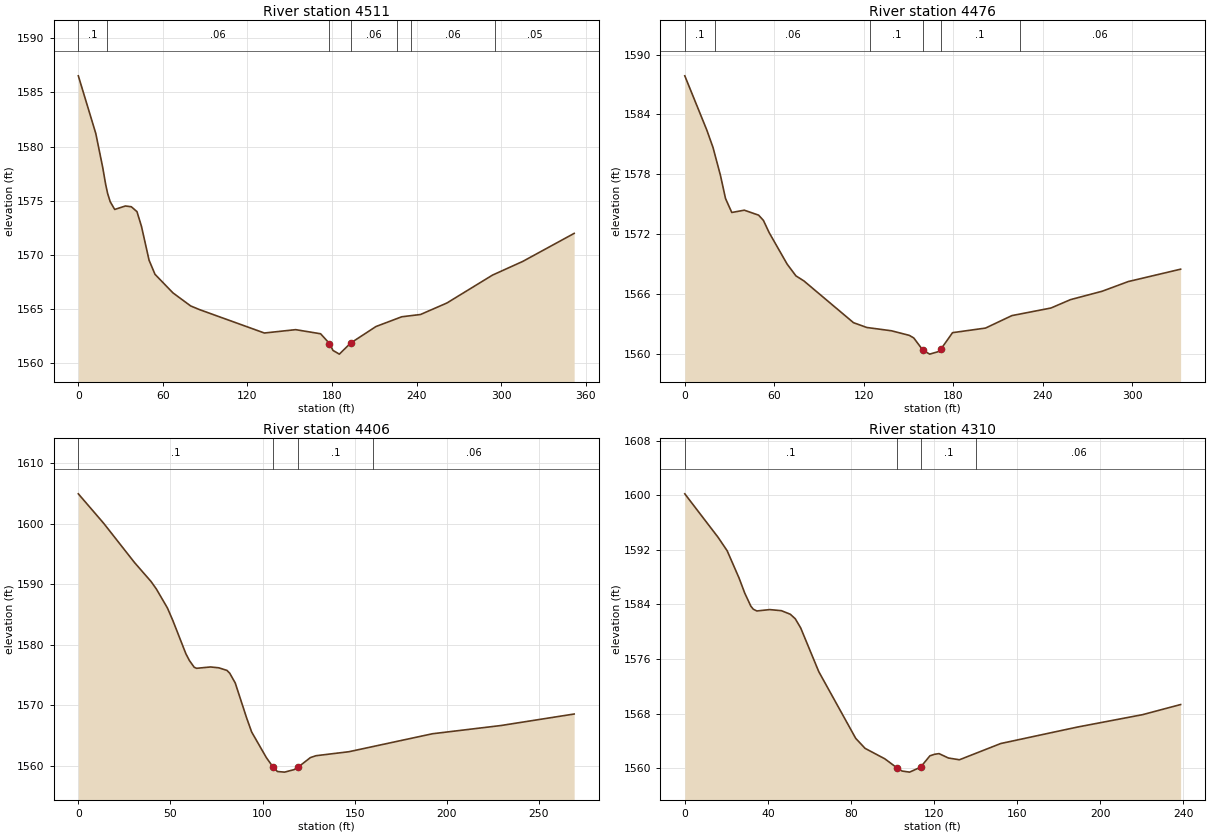
Type RM Length L Ch R = 1 ,4511    ,35.2,35.4,37
XS GIS Cut Line= 4
2152184.41118283659877.8839765482152275.69300403659848.138673714
2152419.66270965659916.7595216512152504.29931591659870.735858259
#Sta/Elev= 30
       0 1586.53    12.4  1581.2    17.3 1578.07    19.4  1576.5    20.8 1575.66
    22.6 1574.91    25.8 1574.19    33.4 1574.51    37.6 1574.44    41.6 1573.99
    44.8 1572.63    50.2  1569.5    54.4  1568.2    67.1 1566.49    79.7 1565.28
      86 1564.94     132 1562.78   154.2 1563.09   171.9 1562.71   178.2 1561.81
   180.7 1561.17   185.2 1560.83   193.2 1561.85   211.2 1563.38   229.5 1564.28
   242.8 1564.49   261.5 1565.55   293.9 1568.13   315.3 1569.39   351.8 1571.98
#Mann= 7 ,-1,0
       0      .1       0      20     .06       0   178.2    .045       0
   193.2     .06       0  226.01      .1       0  236.01     .06       0
  295.49     .05       0
Bank Sta=178.2,193.2
XS Rating Curve= 0 ,0
Exp/Cntr(USF)=0,0
Exp/Cntr=0.3,0.1

Type RM Length L Ch R = 1 ,4476    ,78.5,70.1,59.6
XS GIS Cut Line= 4
2152198.07675383659904.9824762812152269.22241818 659882.91807266
2152423.90591358659955.9015272042152498.48433023 659911.40516097
#Sta/Elev= 30
       0 1587.87    14.8 1582.42    18.9  1580.7    23.9  1577.9    27.3 1575.58
    31.5 1574.18    39.9 1574.41    49.5 1573.91    52.7 1573.39    56.6 1572.15
    68.6 1569.01    74.5 1567.83    79.8 1567.33   113.1 1563.14     122 1562.66
   138.5 1562.33   150.5 1561.87   153.5 1561.61   159.7 1560.37   164.2 1559.99
   170.6 1560.27   171.6 1560.47   179.5 1562.14   201.6  1562.6   219.3 1563.85
   245.5 1564.61   258.6 1565.45   279.8 1566.29   297.3 1567.26   332.4  1568.5
#Mann= 6 ,-1,0
       0      .1       0      20     .06       0  124.49      .1       0
   159.7    .045       0   171.6      .1       0  224.49     .06       0
Bank Sta=159.7,171.6
XS Rating Curve= 0 ,0
Exp/Cntr(USF)=0,0
Exp/Cntr=0.3,0.1

Type RM Length L Ch R = 1 ,4406    ,101.6,95.6,87.2
XS GIS Cut Line= 3
 2152263.8170884660037.6863086512152469.43689793659935.832775092
2152500.04077656659910.488938104
#Sta/Elev= 30
       0 1604.96    13.8 1600.08    30.5 1593.61    39.5 1590.47    42.4 1589.22
    48.4 1586.09    51.4 1583.97    58.4 1578.54    60.3 1577.43    62.9 1576.32
    64.2 1576.14    71.8 1576.36    76.3 1576.22    80.7 1575.79    82.2 1575.33
    85.2 1573.71    91.3 1568.01    94.1 1565.62   102.1 1561.38   105.8  1559.8
   108.1 1559.09     112 1558.99   117.1  1559.4   119.31559.811     126 1561.39
     129  1561.7   146.9 1562.36   192.3 1565.33   229.5 1566.69   269.2 1568.59
#Mann= 4 ,-1,0
       0      .1       0   105.8    .045       0   119.3      .1       0
     160     .06       0
Bank Sta=105.8,119.3
XS Rating Curve= 0 ,0
Exp/Cntr(USF)=0,0
Exp/Cntr=0.3,0.1

Type RM Length L Ch R = 1 ,4310    ,108.5,109.1,108.9
XS GIS Cut Line= 3
2152383.31702279660100.7886539612152431.85218282660064.926950346
2152510.26049015659904.767885657
#Sta/Elev= 30
       0 1600.19      16 1593.83    20.4 1591.85    26.1 1587.87    28.9 1585.62
    31.8 1583.73      33 1583.28    34.7 1583.03    40.9 1583.23    46.5 1583.07
    50.8 1582.55    53.2 1581.88    55.8 1580.54    64.5 1574.14    82.3 1564.36
    86.8  1562.9    96.3 1561.37   102.3 1560.01   104.6 1559.58   108.2 1559.42
   113.5 1560.14     118 1561.81   120.2 1562.03   122.4 1562.13   126.9 1561.49
   132.2 1561.23   152.1 1563.61     189 1566.02   220.4 1567.84   238.7 1569.32
#Mann= 4 ,-1,0
       0      .1       0   102.3    .045       0   113.5      .1       0
  140.35     .06       0
Bank Sta=102.3,113.5
XS Rating Curve= 0 ,0
Exp/Cntr(USF)=0,0
Exp/Cntr=0.3,0.1