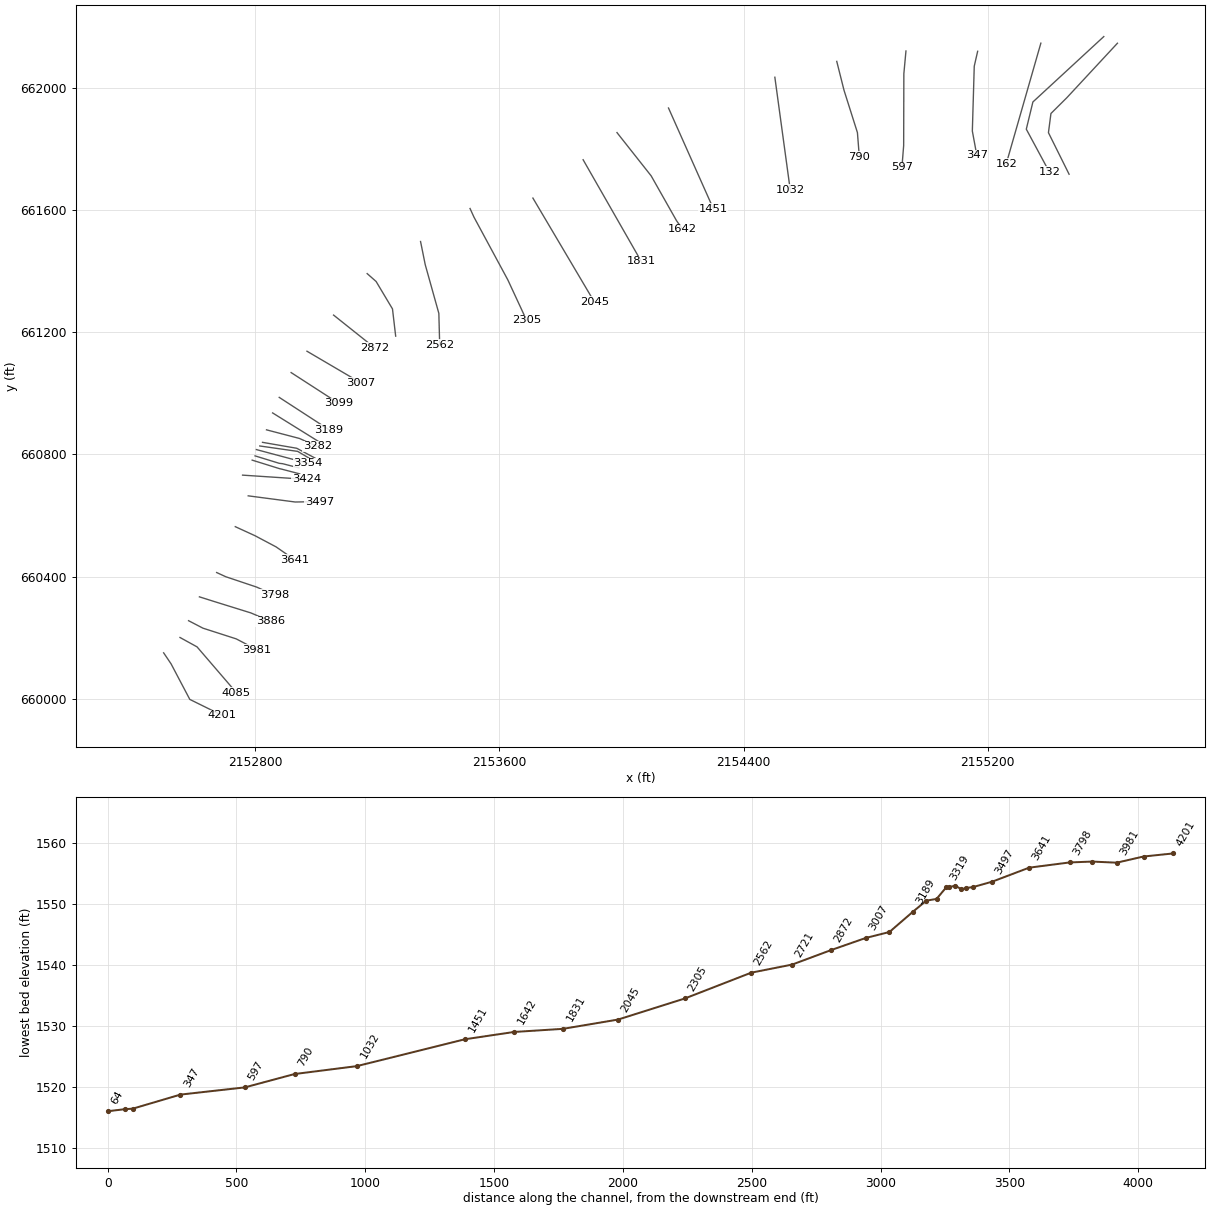
HEC-RAS study COWRN.prj: COWRN

--- COWRN.g01 (geometry) --- (continued)

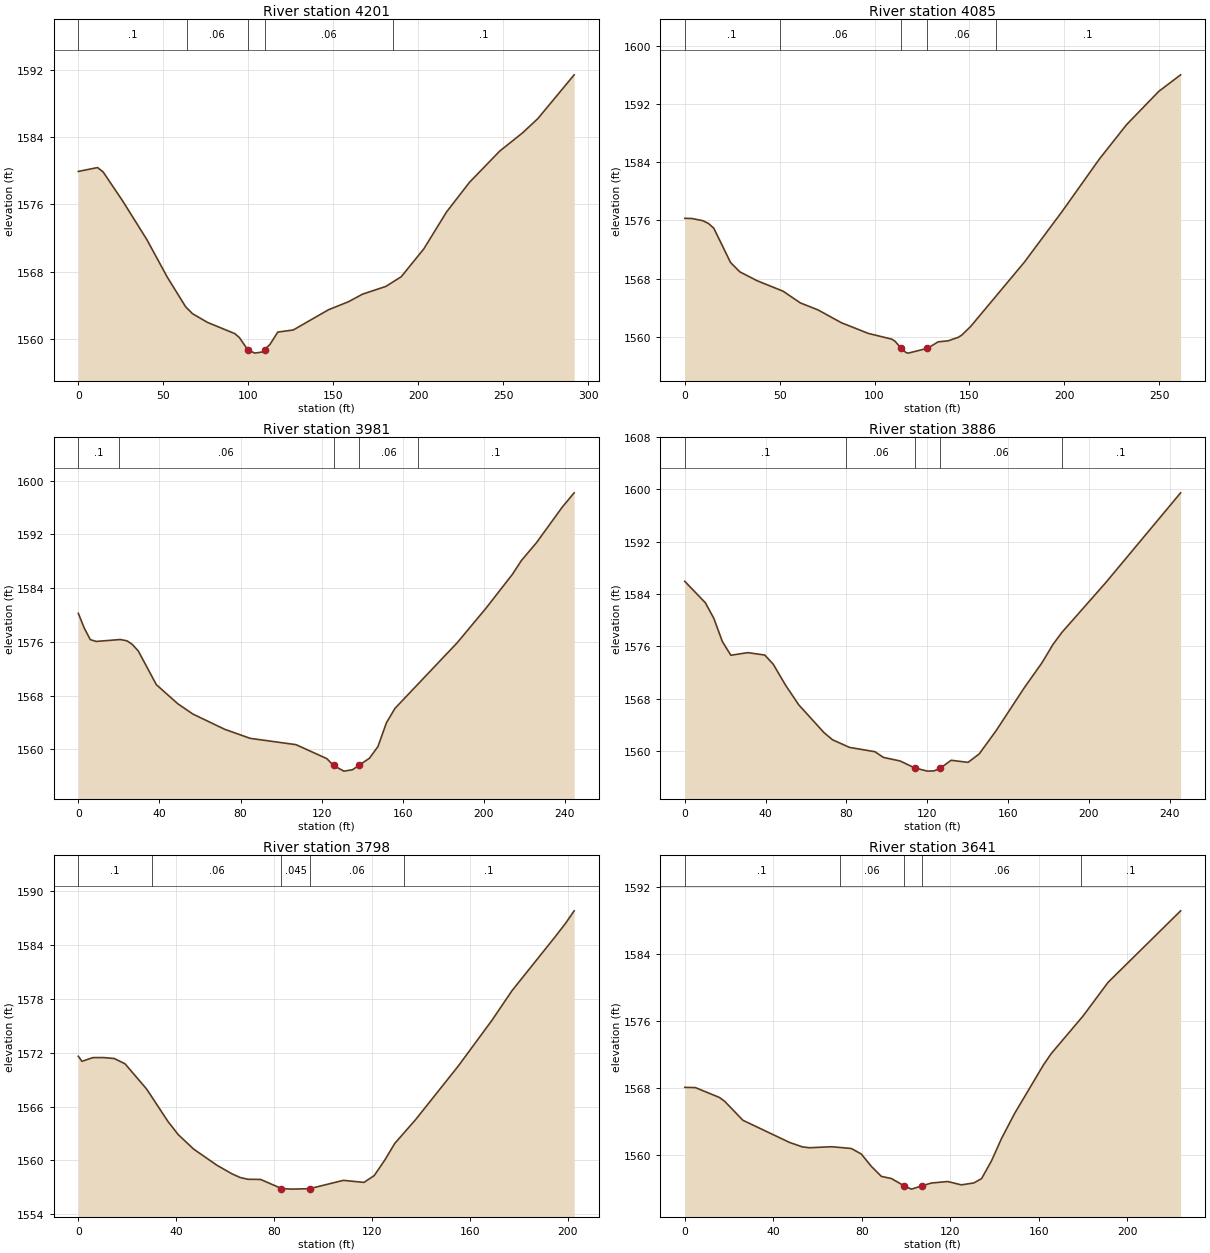
Type RM Length L Ch R = 1 ,4201    ,113.2,116,117.9
XS GIS Cut Line= 4
2152501.27765565660150.5772327662152525.64968723660114.367357271
2152586.92793807659998.0779494322152691.37950199659946.548511228
#Sta/Elev= 30
       0 1579.94    11.3  1580.4    14.6 1579.88    26.2 1576.38    40.3 1571.81
    52.3 1567.34    63.1  1563.8    67.1 1562.98      76 1561.93      92  1560.6
    94.7 1560.13    99.7 1558.66   103.8 1558.27   108.3 1558.41  109.551558.664
   112.8 1559.34   117.3 1560.78   126.4 1561.03   147.1 1563.44   158.9  1564.4
   167.1  1565.3   180.9 1566.23   189.9 1567.38   203.2 1570.71   216.6 1575.12
     230 1578.63   247.8 1582.36   261.2 1584.53   270.2 1586.23   291.6 1591.46
#Mann= 5 ,-1,0
       0      .1       0   63.65     .06       0    99.7    .045       0
  109.55     .06       0  185.09      .1       0
Bank Sta=99.7,109.55
XS Rating Curve= 0 ,0
Exp/Cntr(USF)=0,0
Exp/Cntr=0.3,0.1

Type RM Length L Ch R = 1 ,4085    ,98.1,104.1,109.8
XS GIS Cut Line= 3
2152554.79361528660200.8187414072152610.67061005660170.045903704
2152739.43064149660020.230772781
#Sta/Elev= 30
       0 1576.28     3.7 1576.26     9.6 1575.95    12.5 1575.57    15.3 1574.92
    24.1 1570.22      29 1568.93    38.1 1567.71    51.8 1566.27    60.9 1564.66
    70.2  1563.7    82.5 1561.94    96.7 1560.47   109.1 1559.68   110.9 1559.37
   113.7 1558.52   116.5 1557.85   117.7 1557.76   127.9 1558.42   133.5 1559.31
   138.8 1559.45     144 1559.92   145.9 1560.22   150.6 1561.41   178.9 1570.24
   198.8 1577.21   218.6 1584.47   232.8 1589.15   249.8 1593.73   261.3    1596
#Mann= 5 ,-1,0
       0      .1       0      50     .06       0   113.7    .045       0
   127.9     .06       0  163.79      .1       0
Bank Sta=113.7,127.9
XS Rating Curve= 0 ,0
Exp/Cntr(USF)=0,0
Exp/Cntr=0.3,0.1

Type RM Length L Ch R = 1 ,3981    ,95,95.2,95.2
XS GIS Cut Line= 4
 2152582.9035343660255.7909761572152629.90673807660231.349310198
2152738.95417081660196.2535847182152807.26549362660160.531149855
#Sta/Elev= 30
       0 1580.25     2.9 1578.07     5.9 1576.33     8.8 1576.06    20.7 1576.35
      24 1576.15    26.6 1575.63    29.6 1574.63    38.5 1569.62      49  1566.8
    56.5 1565.25    72.2 1562.98    84.8 1561.63   107.4 1560.69   122.6 1558.61
  125.89 1557.59     131 1556.75   135.2 1556.95   138.4  1557.6   143.6 1558.67
   147.8  1560.4     152 1563.96   156.2 1566.09     187  1575.9     201 1580.97
   214.1 1586.04   218.6 1588.12     226 1590.76   238.8 1596.09   244.6 1598.19
#Mann= 5 ,-1,0
       0      .1       0      20     .06       0  125.89    .045       0
   138.4     .06       0  167.53      .1       0
Bank Sta=125.89,138.4
XS Rating Curve= 0 ,0
Exp/Cntr(USF)=0,0
Exp/Cntr=0.3,0.1

Type RM Length L Ch R = 1 ,3886    ,87.9,87.6,87.5
XS GIS Cut Line= 4
2152618.40816141 660333.887653462152666.03807456660318.846628255
2152786.99298559660281.2440652412152850.29063333660254.295561748
#Sta/Elev= 30
       0 1585.95    10.2 1582.67    14.4 1580.28    18.6 1576.74    22.8 1574.65
    31.2 1575.05    39.6 1574.68    43.8 1573.27    49.9 1570.06    56.4 1567.07
    68.9 1562.82    73.1 1561.73    81.5 1560.56    94.1  1559.9    98.3 1559.03
   106.6 1558.48   113.7 1557.43   120.1 1556.93   123.4 1556.97   126.5 1557.38
   131.8 1558.59   140.2 1558.27   145.7 1559.56     154 1563.08     168 1569.67
   176.8 1573.51   182.2 1576.29   186.6 1578.13   208.1 1585.67   245.4 1599.49
#Mann= 5 ,-1,0
       0      .1       0   79.95     .06       0   113.7    .045       0
   126.5     .06       0  186.61      .1       0
Bank Sta=113.7,126.5
XS Rating Curve= 0 ,0
Exp/Cntr(USF)=0,0
Exp/Cntr=0.3,0.1

Type RM Length L Ch R = 1 ,3798    ,158.6,157.3,155.9
XS GIS Cut Line= 4
2152674.81200593660413.4797451732152704.89405634660399.692138735
 2152805.7942671660365.8498320222152863.45153038660340.154747296
#Sta/Elev= 30
       0 1571.61     1.5 1571.05     5.9 1571.46    10.3 1571.47    14.7 1571.36
    19.1 1570.77    27.9 1567.96    36.6 1564.35    40.8 1562.88    47.1 1561.26
    56.6 1559.46    62.9 1558.48    66.1 1558.09    69.3 1557.89    74.5 1557.87
      83 1556.86    87.2 1556.79    94.5 1556.84   108.3 1557.77   116.7 1557.54
   120.9  1558.3   125.2 1560.02   129.3 1561.89   137.8 1564.54   155.3 1570.54
   169.1 1575.66   177.2 1578.93   194.7  1584.9   199.1 1586.45   202.6 1587.84
#Mann= 5 ,-1,0
       0      .1       0      30     .06       0      83    .045       0
    94.5     .06       0  133.09      .1       0
Bank Sta=83,94.5
XS Rating Curve= 0 ,0
Exp/Cntr(USF)=0,0
Exp/Cntr=0.3,0.1

Type RM Length L Ch R = 1 ,3641    ,139.9,143.6,146.6
XS GIS Cut Line= 4
2152735.83156506660563.6654472562152800.38745723660534.060197344
2152869.46637369660497.4648189812152931.14397768660454.701680219
#Sta/Elev= 30
       0  1568.1     4.8 1568.07    15.6  1566.9      18 1566.44    26.3 1564.16
    47.4 1561.51    53.2 1560.98    56.4 1560.88    66.4    1561    75.3 1560.79
    79.8 1560.13    84.4 1558.64    88.9 1557.45    93.4  1557.2   99.311556.302
   102.5 1555.93   107.1 1556.31   111.5 1556.66   118.9 1556.84   125.1 1556.44
   130.7 1556.67   134.2 1557.19   138.7 1559.32   143.2 1561.98   149.2 1565.01
   162.2 1570.79   165.7 1572.14   180.1 1576.64   191.4 1580.66   224.2 1589.21
#Mann= 5 ,-1,0
       0      .1       0      70     .06       0   99.31    .045       0
   107.1     .06       0  179.19      .1       0
Bank Sta=99.31,107.1
XS Rating Curve= 0 ,0
Exp/Cntr(USF)=0,0
Exp/Cntr=0.3,0.1

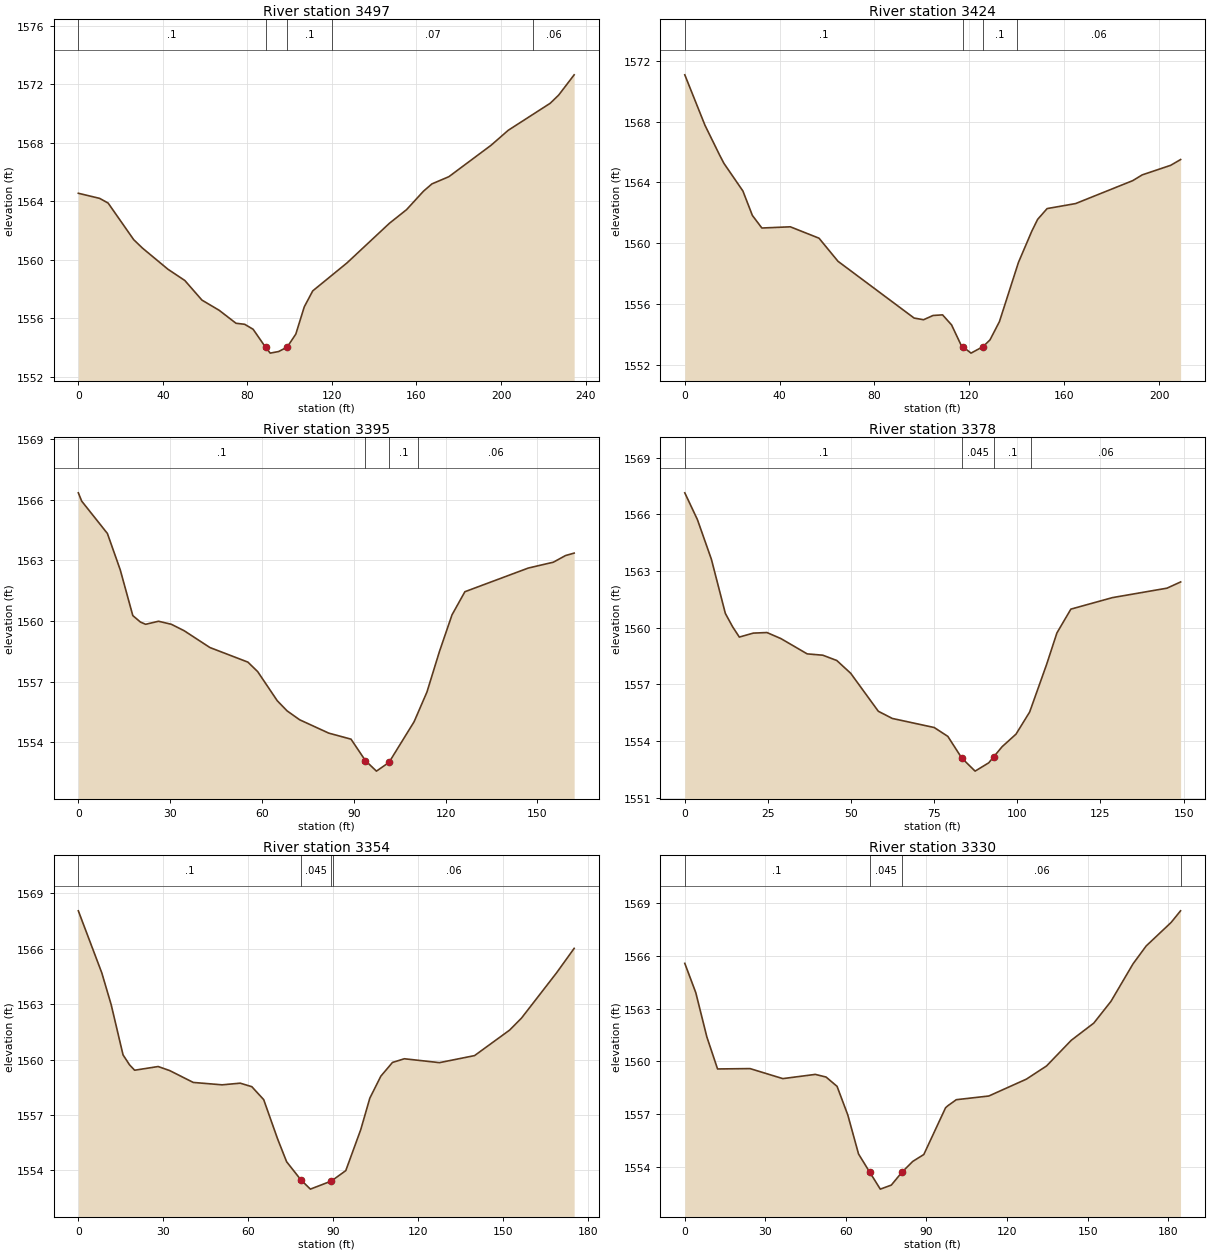
Type RM Length L Ch R = 1 ,3497    ,72.5,73.2,73.8
XS GIS Cut Line= 3
2152778.17689063660664.6040366692152932.06886148660644.410067643
2153011.45205006660645.802755162
#Sta/Elev= 30
       0 1564.55    10.1  1564.2    14.1 1563.88    26.2 1561.38    30.3 1560.81
    42.4 1559.36    50.4 1558.59    58.5 1557.25    66.6 1556.56    74.6 1555.67
    78.7  1555.6    82.7 1555.26   88.591554.032    90.8 1553.63    94.8 1553.74
    98.8 1554.04   102.9 1554.93   106.9 1556.79   110.9 1557.88   127.1 1559.79
   147.2  1562.5   155.3 1563.43   163.3 1564.69   167.3 1565.19   175.3 1565.68
   195.3 1567.83   203.4 1568.85   223.3  1570.7   227.3 1571.26   234.6 1572.64
#Mann= 5 ,-1,0
       0      .1       0   88.59    .045       0    98.8      .1       0
     120     .07       0  215.21     .06       0
Bank Sta=88.59,98.8
XS Rating Curve= 0 ,0
Exp/Cntr(USF)=0,0
Exp/Cntr=0.3,0.1

Type RM Length L Ch R = 1 ,3424    ,30.6,28.7,27.1
XS GIS Cut Line= 2
2152759.73301128660732.402667885  2152968.427236660718.615061447
#Sta/Elev= 30
       0 1571.09     8.5 1567.77    14.7  1565.8    16.5 1565.26    24.5 1563.44
    28.5 1561.83    32.5    1561    44.5 1561.08    56.6 1560.33    64.6 1558.81
    96.7 1555.07   100.7 1554.96   104.7 1555.24   108.7 1555.28   112.5 1554.62
   116.7 1553.23   117.2 1553.19   120.7 1552.76   125.8 1553.19   128.7 1553.63
   132.7 1554.84   140.7 1558.73   146.3 1560.78   148.8 1561.57   152.8 1562.28
   164.8 1562.61   188.9 1564.12   192.9  1564.5   204.9 1565.13   209.1 1565.51
#Mann= 4 ,-1,0
       0      .1       0   117.2    .045       0   125.8      .1       0
     140     .06       0
Bank Sta=117.2,125.8
XS Rating Curve= 0 ,0
Exp/Cntr(USF)=0,0
Exp/Cntr=0.3,0.1

Type RM Length L Ch R = 1 ,3395    ,17.3,17.8,18.3
XS GIS Cut Line= 4
2152791.13799979660781.5192266582152880.73550681 660753.59932362
2152887.58857392660752.076419818 2152946.7280049660736.593564496
#Sta/Elev= 30
       0 1566.34     1.1 1565.93     9.5 1564.33    13.7 1562.53    17.8 1560.27
    20.3 1559.95      22 1559.84    26.2 1559.99    30.4 1559.84    34.6 1559.52
      43 1558.69    55.4 1557.97    58.6  1557.5      65 1556.06    68.2 1555.56
    72.3 1555.12    81.8 1554.46    89.1 1554.16    93.8  1553.1    97.4 1552.58
   101.5 1553.01   109.7 1555.02   113.9 1556.49     118  1558.5   122.1 1560.31
   126.3 1561.45     147 1562.62   155.2 1562.91   159.2 1563.24     162 1563.36
#Mann= 4 ,-1,0
       0      .1       0    93.8    .045       0   101.5      .1       0
  110.87     .06       0
Bank Sta=93.8,101.5
XS Rating Curve= 0 ,0
Exp/Cntr(USF)=0,0
Exp/Cntr=0.3,0.1

Type RM Length L Ch R = 1 ,3378    ,24.6,23.7,22.8
XS GIS Cut Line= 4
 2152800.5292399660795.4791781772152879.72023761660771.112717343
2152890.88819882660769.843630842 2152944.1898319660756.137496623
#Sta/Elev= 30
       0 1567.14     3.8 1565.72       8 1563.62    12.2 1560.75    14.4 1560.04
    16.4  1559.5    20.6 1559.71    24.7 1559.74    28.9 1559.42    36.8 1558.61
    41.5 1558.54    45.7 1558.26    49.9 1557.58    58.2 1555.57    62.4 1555.19
      75 1554.71    79.1 1554.24    83.3 1553.09    87.3  1552.4    91.4 1552.84
   92.851553.148    95.4 1553.69    99.6 1554.36   103.7 1555.53   108.8 1558.05
   111.9 1559.72   116.1 1560.98   128.6 1561.59     145 1562.09   149.1 1562.42
#Mann= 4 ,-1,0
       0      .1       0    83.3    .045       0   92.85      .1       0
  104.09     .06       0
Bank Sta=83.3,92.85
XS Rating Curve= 0 ,0
Exp/Cntr(USF)=0,0
Exp/Cntr=0.3,0.1

Type RM Length L Ch R = 1 ,3354    ,22.1,23.4,24.6
XS GIS Cut Line= 2
2152804.92819711660816.0811407052152974.16260825660770.820774936
#Sta/Elev= 30
       0 1568.04     8.3 1564.68    11.6 1562.97    15.8 1560.25    18.1 1559.71
    19.9 1559.42    28.2 1559.62    32.3  1559.4    40.6 1558.76    50.8 1558.63
    57.2 1558.72    61.3 1558.53    65.5 1557.83    70.4 1555.71    73.6 1554.47
    78.71553.481      82 1552.99    89.41553.427    94.5 1553.99    99.8 1556.21
     103 1557.91   106.9  1559.1     111 1559.84   115.2 1560.04   127.6 1559.83
     140 1560.21   152.4 1561.59   156.6 1562.24     169 1564.69   175.2 1566.01
#Mann= 4 ,-1,0
       0      .1       0    78.7    .045       0    89.4      .1       0
      90     .06       0
Bank Sta=78.7,89.4
XS Rating Curve= 0 ,0
Exp/Cntr(USF)=0,0
Exp/Cntr=0.3,0.1

Type RM Length L Ch R = 1 ,3330    ,11.4,11.1,10.8
XS GIS Cut Line= 3
2152816.07930172660827.8881926452152940.05334709660810.177614735
2152991.21723883660780.004037556
#Sta/Elev= 30
       0 1565.57     4.1  1563.9     8.2 1561.39    12.2 1559.56    24.3 1559.58
    36.5 1559.01    48.6 1559.25    52.6  1559.1    56.7 1558.57    60.7 1556.94
    64.7 1554.72    68.8  1553.7    72.8 1552.72    76.9 1552.95    80.9 1553.69
    84.9  1554.3      89 1554.69    97.1 1557.35    97.9 1557.46   101.1 1557.81
   113.2 1558.02   127.2 1558.98   134.7 1559.73   143.9 1561.19   152.3 1562.17
   158.7 1563.41   166.9 1565.54   171.8 1566.56   181.1  1567.9   184.6 1568.56
#Mann= 4 ,-1,0
       0      .1       0    68.8    .045       0    80.9     .06       0
  184.63      .1       0
Bank Sta=68.8,80.9
XS Rating Curve= 0 ,0
Exp/Cntr(USF)=0,0
Exp/Cntr=0.3,0.1

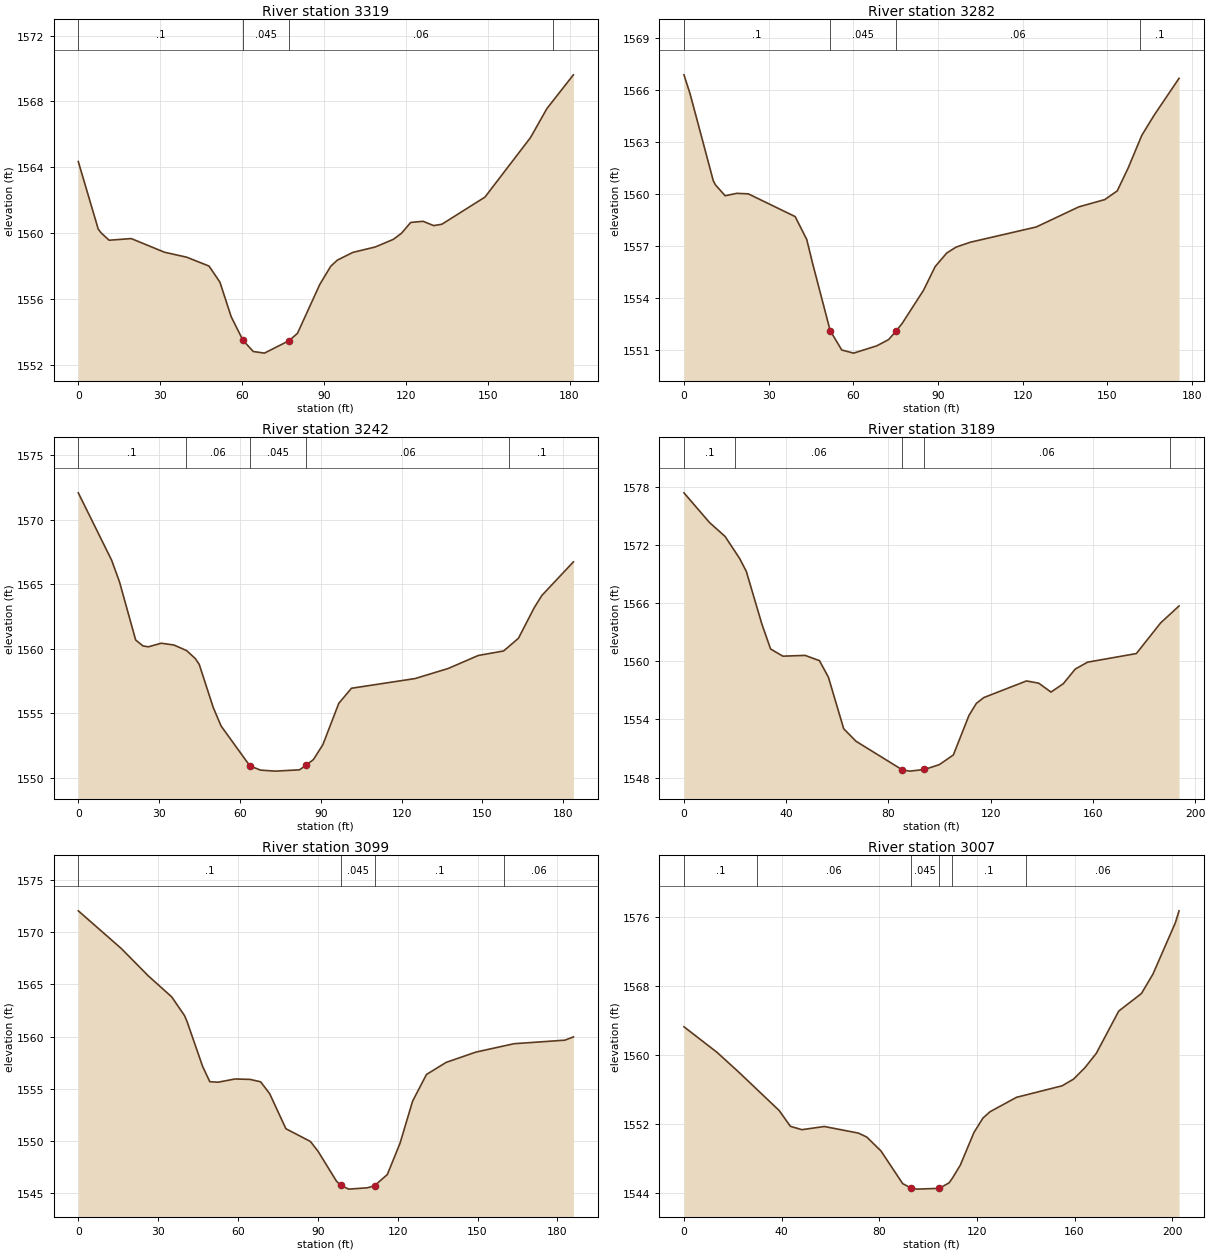
Type RM Length L Ch R = 1 ,3319    ,38.7,37.8,37.3
XS GIS Cut Line= 3
2152825.02167688660839.7784816332152937.20265653660820.350490742
2152996.74004797 660788.38831218
#Sta/Elev= 30
       0 1564.35     7.3 1560.25     8.4 1560.01    11.3 1559.57    19.4 1559.67
    31.6 1558.84    39.7 1558.54    47.9    1558    51.9 1557.02      56 1554.93
    60.3  1553.5    64.1 1552.81    68.2 1552.71   77.25 1553.47    80.3 1553.91
    88.5 1556.89    92.5 1557.99    94.9 1558.36   100.6 1558.83   108.8 1559.16
   115.4 1559.62   118.4 1559.99   121.8 1560.65   126.3 1560.72   130.2 1560.46
   133.2 1560.54     149 1562.19   165.7 1565.81   171.7 1567.57   181.4 1569.62
#Mann= 4 ,-1,0
       0      .1       0    60.3    .045       0   77.25     .06       0
  173.85      .1       0
Bank Sta=60.3,77.25
XS Rating Curve= 0 ,0
Exp/Cntr(USF)=0,0
Exp/Cntr=0.3,0.1

Type RM Length L Ch R = 1 ,3282    ,42.8,39.6,37.6
XS GIS Cut Line= 3
2152838.07376164660880.7332548552152945.86777561660852.531332595
2153004.15174828660826.209538485
#Sta/Elev= 30
       0 1566.85     2.2 1565.74    10.4 1560.74    11.2  1560.5    14.6 1559.88
    18.7 1560.02    22.8 1559.99    39.4 1558.68    43.5 1557.36    45.6 1555.97
    51.8 1552.11    55.9 1550.99    60.1 1550.81    68.3 1551.23    72.5 1551.59
   75.09 1552.07    77.3 1552.52    84.9 1554.44      89  1555.8    93.1 1556.58
    96.4 1556.92   101.4  1557.2   124.8 1558.08   139.9 1559.24   149.1 1559.66
   153.5 1560.16   157.4 1561.49   162.2 1563.36   166.6 1564.53   175.4 1566.65
#Mann= 4 ,-1,0
       0      .1       0    51.8    .045       0   75.09     .06       0
  161.42      .1       0
Bank Sta=51.8,75.09
XS Rating Curve= 0 ,0
Exp/Cntr(USF)=0,0
Exp/Cntr=0.3,0.1

Type RM Length L Ch R = 1 ,3242    ,53.7,53.4,53.5
XS GIS Cut Line= 2
2152858.05993084660936.1195020932153014.17539538660839.039297255
#Sta/Elev= 30
       0 1572.08    12.4 1566.85    15.3 1565.18    21.3 1560.68      24 1560.22
      26 1560.15    30.8 1560.43    35.5 1560.29    40.2 1559.86    43.4 1559.25
    44.9 1558.79    50.1 1555.45      53 1554.02    63.7 1550.93    67.6  1550.6
    73.1 1550.52    82.1 1550.62    84.6 1550.98    87.3 1551.42    90.8 1552.57
    96.7 1555.77   101.4 1556.94     125 1557.69   137.3 1558.47   148.5 1559.48
   157.9 1559.83   163.4 1560.81   169.2 1563.16   172.1 1564.13   183.8 1566.73
#Mann= 5 ,-1,0
       0      .1       0      40     .06       0    63.7    .045       0
    84.6     .06       0     160      .1       0
Bank Sta=63.7,84.6
XS Rating Curve= 0 ,0
Exp/Cntr(USF)=0,0
Exp/Cntr=0.3,0.1

Type RM Length L Ch R = 1 ,3189    ,89.6,89.9,89.9
XS GIS Cut Line= 2
2152879.74785823 660986.972019492153042.19093045660881.496830236
#Sta/Elev= 30
       0 1577.42      10 1574.35    16.1 1572.91    21.8 1570.63    24.4  1569.3
    30.5 1563.85    33.9 1561.28    38.7 1560.54    47.4 1560.62      53 1560.08
    56.5 1558.38    62.5 1553.04    67.3 1551.75    85.5 1548.78    88.4 1548.66
    94.1 1548.83    99.9 1549.33   105.4 1550.33   111.5 1554.41   114.4 1555.66
   117.3 1556.26     134 1557.98   138.8 1557.75   143.6 1556.83   148.4 1557.69
   153.1 1559.21   157.9 1559.92     177 1560.81   186.5 1563.98   193.7 1565.73
#Mann= 5 ,-1,0
       0      .1       0      20     .06       0    85.5    .045       0
    94.1     .06       0     190      .1       0
Bank Sta=85.5,94.1
XS Rating Curve= 0 ,0
Exp/Cntr(USF)=0,0
Exp/Cntr=0.3,0.1

Type RM Length L Ch R = 1 ,3099    ,90.8,91.4,91.7
XS GIS Cut Line= 2
2152918.66651095  661068.19355562153074.90516027660967.230673908
#Sta/Elev= 30
       0 1572.06    16.1 1568.46    26.4  1565.8    35.1 1563.81    39.9 1562.02
    40.9 1561.42    46.7 1557.15    49.4 1555.68    52.5 1555.63    58.9 1555.94
    64.5  1555.9    68.5 1555.67    71.9 1554.53      78 1551.17    87.2 1549.95
    90.1    1549      97 1546.14    98.7 1545.73   101.6 1545.38   108.7 1545.51
   111.3 1545.71   116.1 1546.78   120.9  1549.8   125.6 1553.82   130.8 1556.37
   138.2 1557.53   149.4 1558.52   163.7 1559.32   182.8 1559.66     186 1559.97
#Mann= 4 ,-1,0
       0      .1       0    98.7    .045       0   111.3      .1       0
     160     .06       0
Bank Sta=98.7,111.3
XS Rating Curve= 0 ,0
Exp/Cntr(USF)=0,0
Exp/Cntr=0.3,0.1

Type RM Length L Ch R = 1 ,3007    ,136.5,135.5,134.5
XS GIS Cut Line= 2
2152970.55804791661138.1343228062153145.40996592661035.479325778
#Sta/Elev= 30
       0 1563.28    13.6  1560.3    22.3 1558.05      39 1553.55    43.6 1551.71
    48.3 1551.32    57.5 1551.69    71.5 1550.92    74.9 1550.46    80.7 1548.85
    89.6 1545.05      931544.542    95.4 1544.41   104.6  1544.5   108.6 1545.14
     110  1545.7   113.2  1547.2   118.8    1551   122.5 1552.68   125.4 1553.41
   136.2 1555.08   154.9 1556.42   159.6  1557.2   164.2 1558.51   168.9 1560.19
   178.1 1565.11   187.4 1567.15   192.1  1569.4   201.3 1575.38   202.8 1576.76
#Mann= 6 ,-1,0
       0      .1       0      30     .06       0      93    .045       0
   104.6     .06       0     110      .1       0     140     .06       0
Bank Sta=93,104.6
XS Rating Curve= 0 ,0
Exp/Cntr(USF)=0,0
Exp/Cntr=0.3,0.1

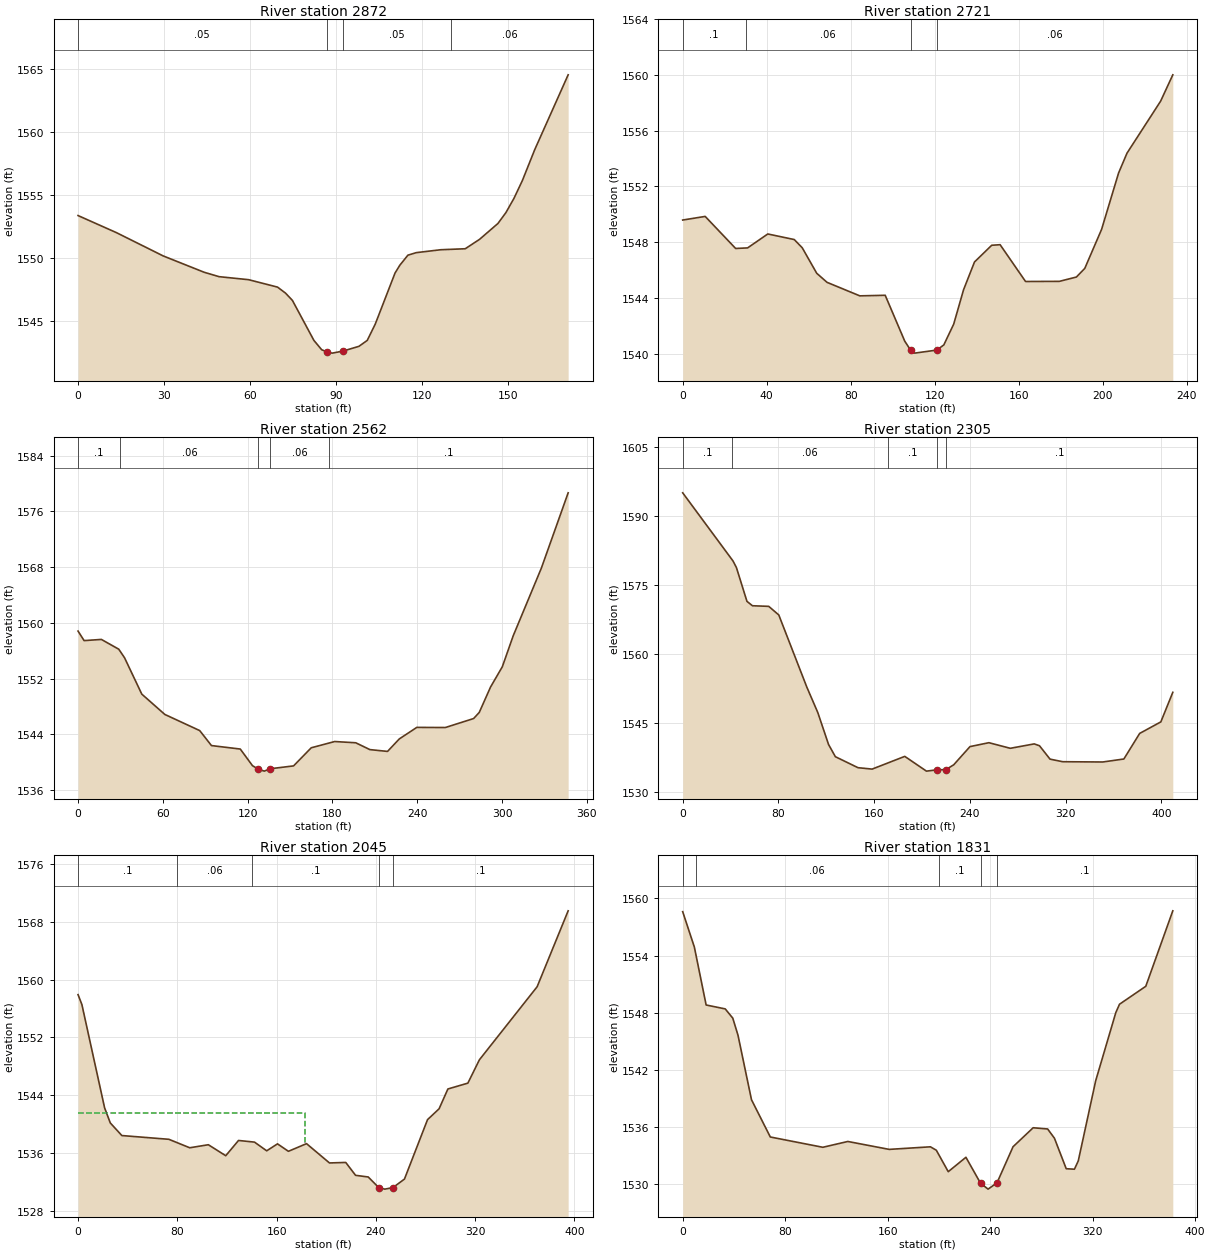
Type RM Length L Ch R = 1 ,2872    ,154.2,150.6,147.9
XS GIS Cut Line= 2
2153057.67285344661256.4603970092153191.37085527661149.919801803
#Sta/Elev= 30
       0 1553.35    13.4 1551.99    29.7 1550.14      44 1548.84    49.2 1548.49
    59.5 1548.25    69.6 1547.66    72.4 1547.18    74.8  1546.6    82.3 1543.42
      85 1542.68    86.7 1542.52    88.7 1542.41    92.4 1542.57      98 1542.95
   100.9 1543.42   103.7 1544.72   110.6 1548.78   112.3 1549.41   115.1  1550.2
     118  1550.4   126.5 1550.63   135.1 1550.71   140.1 1551.46   146.5 1552.72
   149.3 1553.59   152.1 1554.72     155 1556.12   159.3 1558.57     171 1564.54
#Mann= 4 ,-1,0
       0     .05       0    86.7    .045       0    92.4     .05       0
     130     .06       0
Bank Sta=86.7,92.4
XS Rating Curve= 0 ,0
Exp/Cntr(USF)=0,0
Exp/Cntr=0.3,0.1

Type RM Length L Ch R = 1 ,2721    ,160.2,159,155.9
XS GIS Cut Line= 4
2153167.69516744661392.2474301152153196.94160534661366.482711013
2153250.56007483661276.6543660352153261.00523122661187.522364817
#Sta/Elev= 30
       0 1549.59    10.7 1549.85    25.2 1547.55    30.9 1547.59    40.5 1548.59
    53.1 1548.19    56.9  1547.6    63.8 1545.77    68.7 1545.12    84.3 1544.15
    96.4 1544.19   105.7  1540.9  108.46 1540.26   110.4 1540.04     121 1540.26
   124.3 1540.63     129 1542.12   133.7 1544.59   138.9 1546.58   147.1 1547.78
   151.1 1547.82   163.2 1545.18   179.3 1545.19   187.4  1545.5   191.4 1546.12
   199.4 1548.92   207.5 1552.97   211.5 1554.39   227.5 1558.12   233.3 1560.01
#Mann= 4 ,-1,0
       0      .1       0      30     .06       0  108.46    .045       0
     121     .06       0
Bank Sta=108.46,121
XS Rating Curve= 0 ,0
Exp/Cntr(USF)=0,0
Exp/Cntr=0.3,0.1

Type RM Length L Ch R = 1 ,2562    ,253.6,257.6,258.3
XS GIS Cut Line= 4
2153342.47745108661497.3953378032153357.79701379661421.493868015
 2153402.3630144661262.0311470852153405.14838944661158.275926917
#Sta/Elev= 30
       0 1558.82     4.3 1557.45    16.5 1557.62    28.8 1556.22    32.9 1554.99
    45.1 1549.77    61.4 1546.85    86.1 1544.53    94.4 1542.38   114.8 1541.88
   123.4  1539.5   127.6 1538.98   131.8 1538.71   135.9 1539.05   152.5 1539.46
     165 1542.06   181.6 1542.96   196.5 1542.78   206.5  1541.8     219 1541.54
   227.3 1543.33   239.7 1544.99   259.9 1544.97   279.9 1546.26   283.9 1547.14
   291.9 1550.79   300.2 1553.69   307.9 1558.13   327.9 1567.89   346.8 1578.67
#Mann= 5 ,-1,0
       0      .1       0      30     .06       0   127.6    .045       0
   135.9     .06       0  177.43      .1       0
Bank Sta=127.6,135.9
XS Rating Curve= 0 ,0
Exp/Cntr(USF)=0,0
Exp/Cntr=0.3,0.1

Type RM Length L Ch R = 1 ,2305    ,257,259.5,258.9
XS GIS Cut Line= 4
2153504.51921358661605.4140945042153517.41446839661577.044533931
2153628.31365972661371.5801406912153689.35119913 661240.04854167
#Sta/Elev= 30
       0 1595.08      42 1580.26    44.9 1578.81    53.7 1571.45    58.3 1570.49
    71.9 1570.36    80.3 1568.49   103.7  1552.8   112.9 1547.24   121.9 1540.28
   127.6 1537.62   146.5 1535.23   158.3 1534.92   185.6 1537.69   203.7 1534.48
   212.8 1534.77  219.951534.799   226.5 1535.86   240.1 1539.82   255.9 1540.67
   273.8 1539.45   293.8 1540.41   298.2    1540     307 1537.09   317.6 1536.53
   351.1 1536.47   368.7 1537.12   381.9 1542.69   399.6  1545.2   409.6 1551.64
#Mann= 5 ,-1,0
       0      .1       0   41.16     .06       0  171.16      .1       0
   212.8    .045       0  219.95      .1       0
Bank Sta=212.8,219.95
XS Rating Curve= 0 ,0
Exp/Cntr(USF)=0,0
Exp/Cntr=0.3,0.1

Type RM Length L Ch R = 1 ,2045    ,212.8,213.7,213
XS GIS Cut Line= 2
2153710.34072171661639.5596468222153911.40503564661299.638762512
#Sta/Elev= 30
       0 1557.92     3.1 1556.55    21.4 1542.26      26 1540.17    35.3 1538.43
    73.2 1537.91      90 1536.74     105 1537.16     119 1535.64   129.3 1537.75
   142.2 1537.52     152 1536.32   160.7 1537.28   169.5 1536.25   184.1 1537.31
   202.6 1534.64   215.7 1534.71   223.6 1532.93   233.8  1532.7   242.5  1531.2
   247.2 1531.02   253.7 1531.23     263 1532.41   281.6 1540.63   290.9 1542.13
     298 1544.87   314.1 1545.68   323.4 1548.91   369.9 1559.01   394.9 1569.51
#Mann= 5 ,-1,0
       0      .1       0      80     .06       0     140      .1       0
   242.5    .045       0   253.7      .1       0
#XS Ineff= 2 , 0
          183.12 1541.49
Permanent Ineff=
       F       F
Bank Sta=242.5,253.7
XS Rating Curve= 0 ,0
Exp/Cntr(USF)=0,0
Exp/Cntr=0.3,0.1

Type RM Length L Ch R = 1 ,1831    ,189.7,189.3,188.8
XS GIS Cut Line= 2
2153874.74690105661765.0859864532154064.70268934661432.941070085
#Sta/Elev= 30
       0 1558.61     9.1  1554.9    18.3 1548.82    33.2 1548.41    39.1 1547.44
    43.2 1545.63    53.7 1538.88    68.4 1534.97   109.4 1533.89   128.9  1534.5
   161.2 1533.67   193.4 1533.94     198 1533.58   207.3 1531.33   221.1 1532.84
   232.51530.122   238.4  1529.5  245.36 1530.16   257.9 1533.95   273.6 1535.94
   284.9 1535.81   290.2 1534.84   299.4 1531.64   305.8 1531.59   308.8 1532.46
   322.4 1540.87   338.1 1548.02     341  1548.9   361.5 1550.78   382.6  1558.7
#Mann= 5 ,-1,0
       0      .1       0      10     .06       0     200      .1       0
   232.5    .045       0  245.36      .1       0
Bank Sta=232.5,245.36
XS Rating Curve= 0 ,0
Exp/Cntr(USF)=0,0
Exp/Cntr=0.3,0.1

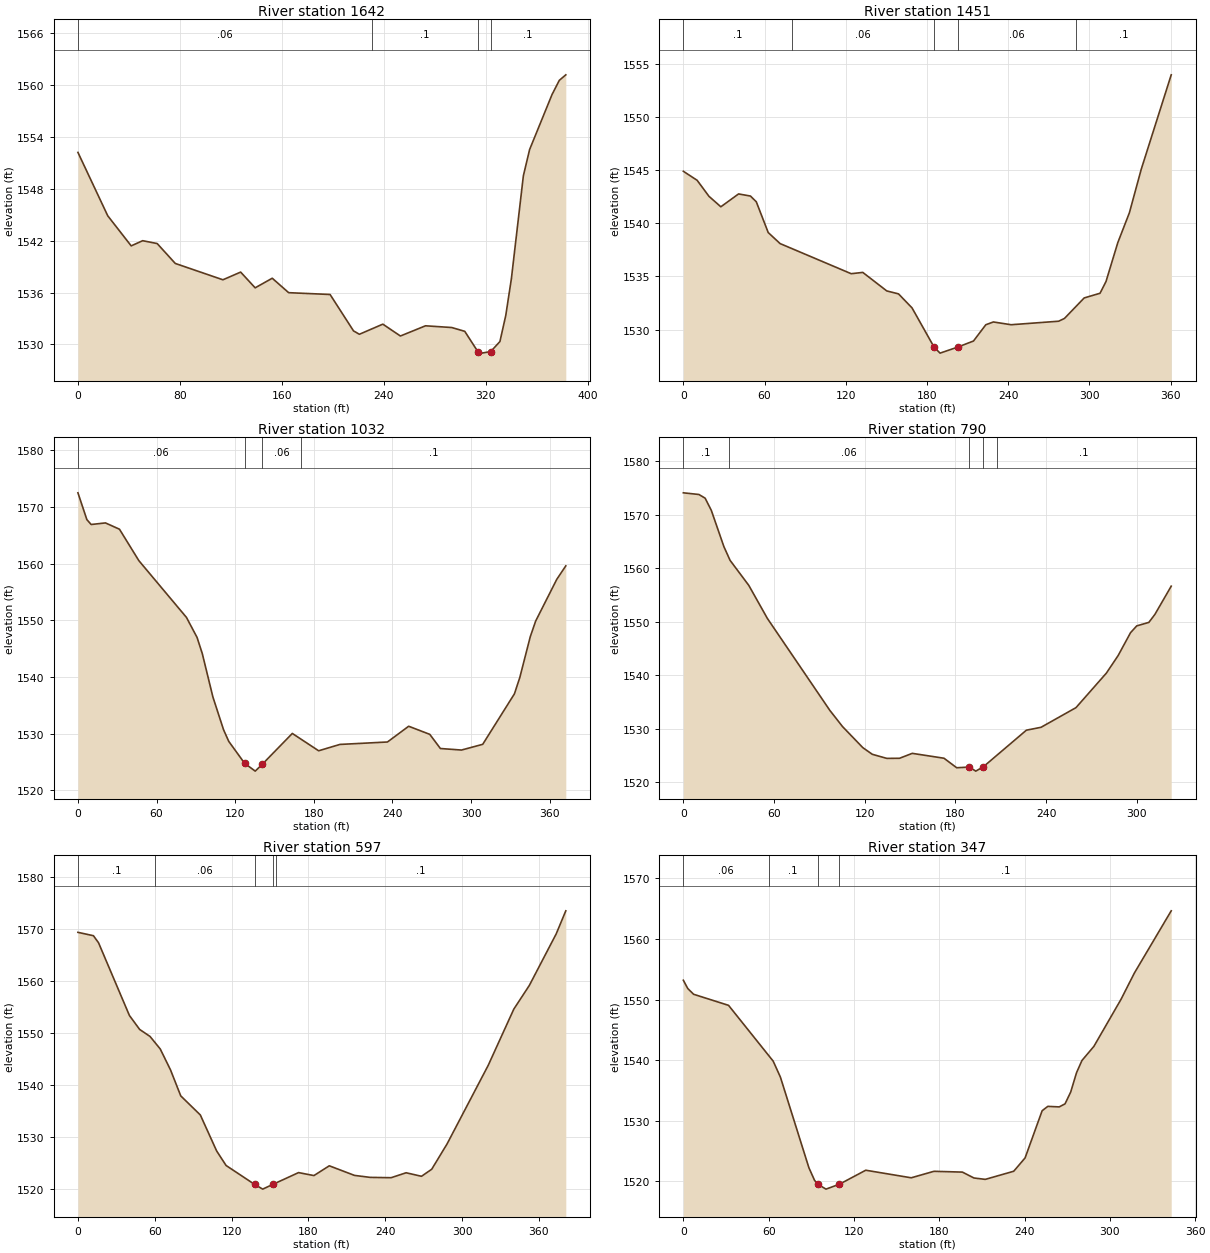
Type RM Length L Ch R = 1 ,1642    ,194,191.3,191.6
XS GIS Cut Line= 4
 2153985.6398732661853.9752547912154097.57677715661712.290250306
2154180.63595051661565.4975528242154199.96159976661537.948223045
#Sta/Elev= 30
       0  1552.2    23.4 1544.87    41.8 1541.39    50.8 1541.99    62.2 1541.66
    76.4 1539.36   113.8 1537.47   127.7 1538.36   139.1 1536.54   152.5 1537.65
   165.4 1535.98   197.9 1535.77   216.3 1531.56   220.9 1531.17   239.3 1532.34
   253.1 1530.97   272.8 1532.15   293.4 1531.95   303.6 1531.51   313.9 1529.16
   316.8 1528.99   323.9 1529.16   331.2 1530.33   335.8 1533.36   340.2  1537.6
   349.6  1549.5   354.5 1552.53   372.1 1558.89   377.8 1560.53   382.9 1561.17
#Mann= 4 ,-1,0
       0     .06       0  230.57      .1       0   313.9    .045       0
   323.9      .1       0
Bank Sta=313.9,323.9
XS Rating Curve= 0 ,0
Exp/Cntr(USF)=0,0
Exp/Cntr=0.3,0.1

Type RM Length L Ch R = 1 ,1451    ,418.3,418.8,408.6
XS GIS Cut Line= 2
2154154.32432872661934.4569416852154300.99019263661605.133590827
#Sta/Elev= 30
       0 1544.89    10.2 1544.04    18.9 1542.54    27.7 1541.55    40.8 1542.76
    49.6 1542.56    53.9 1542.02    62.7 1539.13    71.5 1538.09     124 1535.26
   132.6 1535.38   150.3 1533.64     159 1533.36     169 1532.04   185.3 1528.35
   189.7 1527.79   202.8 1528.36   214.4 1528.93   223.5 1530.46   229.1 1530.72
   242.2 1530.46   277.3 1530.79   281.6 1531.05   296.2 1532.98   307.9 1533.42
   312.3 1534.52     321 1538.17   329.6 1540.99   338.3 1545.06   360.5 1553.96
#Mann= 5 ,-1,0
       0      .1       0      80     .06       0   185.3    .045       0
   202.8     .06       0     290      .1       0
Bank Sta=185.3,202.8
XS Rating Curve= 0 ,0
Exp/Cntr(USF)=0,0
Exp/Cntr=0.3,0.1

Type RM Length L Ch R = 1 ,1032    ,239.6,242.3,242.5
XS GIS Cut Line= 2
2154502.54328167662035.2334862092154552.93155394661666.319350002
#Sta/Elev= 30
       0  1572.5     6.8 1567.78    10.1 1566.91      21 1567.19    31.7 1566.08
    46.5 1560.53    82.8 1550.52    90.9 1546.99    94.9 1544.13     103 1536.47
   111.1 1530.71   115.1 1528.64   127.2 1524.77   135.3 1523.39   140.71524.607
   163.6 1530.04   183.7 1526.98   199.9  1528.1   236.2 1528.53   252.4 1531.31
   268.5 1529.88   276.6 1527.38   292.7 1527.11   308.9 1528.12   333.1 1537.03
   337.2 1539.91   345.2 1547.12   349.3 1549.87   365.4 1557.23   372.3 1559.61
#Mann= 4 ,-1,0
       0     .06       0   127.2    .045       0   140.7     .06       0
     170      .1       0
Bank Sta=127.2,140.7
XS Rating Curve= 0 ,0
Exp/Cntr(USF)=0,0
Exp/Cntr=0.3,0.1

Type RM Length L Ch R = 1 ,790     ,196.3,192.9,188.1
XS GIS Cut Line= 4
2154705.22790479662087.1257257232154729.04286136661992.492608805
2154772.91251821661853.9898350372154779.17961205661774.397743324
#Sta/Elev= 30
       0 1574.09    10.3 1573.78    14.4 1573.09    18.5 1570.81    26.8 1564.05
    30.9 1561.48    43.3 1556.79    55.6 1550.61    96.9 1533.44   105.3 1530.41
   118.7 1526.48     125 1525.23   134.6 1524.47     143 1524.49   151.4 1525.41
   172.4  1524.5   180.8 1522.72   189.2 1522.85   193.4 1522.09   198.3 1522.87
   226.9 1529.74   236.6 1530.28   259.7 1533.95   279.8  1540.4   287.6 1543.69
   295.8 1547.96   299.9 1549.23   307.9 1549.88   311.9 1551.37   322.7 1556.65
#Mann= 5 ,-1,0
       0      .1       0      30     .06       0   189.2    .045       0
   198.3     .06       0  207.58      .1       0
Bank Sta=189.2,198.3
XS Rating Curve= 0 ,0
Exp/Cntr(USF)=0,0
Exp/Cntr=0.3,0.1

Type RM Length L Ch R = 1 ,597     ,248.9,249.8,248.1
XS GIS Cut Line= 4
2154931.81673133662121.1919322682154924.92292811662046.613515623
2154924.29621873661811.5974967862154918.65583427661740.779336444
#Sta/Elev= 30
       0 1569.33    12.1 1568.68    16.1 1567.32    40.2 1553.33    48.2 1550.64
    56.3 1549.29    64.3 1546.87    72.3 1542.85    80.3 1537.85    95.6 1534.17
   108.3 1527.26   115.7 1524.45  137.951520.816   144.3  1519.9   152.3 1520.82
   172.3 1523.08   184.3 1522.51   196.3 1524.39     216 1522.54   228.3 1522.16
   244.6  1522.1   256.3 1523.05   268.3 1522.37   276.3 1523.73   288.3 1528.61
   320.4 1543.72   340.4 1554.55   352.5  1559.1   373.5 1569.03     381 1573.47
#Mann= 5 ,-1,0
       0      .1       0      60     .06       0  137.95    .045       0
   152.3     .06       0   154.9      .1       0
Bank Sta=137.95,152.3
XS Rating Curve= 0 ,0
Exp/Cntr(USF)=0,0
Exp/Cntr=0.3,0.1

Type RM Length L Ch R = 1 ,347     ,187.7,185.3,180.8
XS GIS Cut Line= 4
2155166.59435989662120.2051014012155155.45285974662071.461038235
 2155149.1857659661859.0761915832155163.80898485661779.693002998
#Sta/Elev= 30
       0 1553.19     3.1 1551.83     7.2 1550.88    31.8 1549.05    63.2 1539.84
    68.3 1537.19    88.3 1522.26    92.3 1520.17   94.421519.566   100.3 1518.72
   109.8 1519.53   128.3 1521.84   160.3 1520.59   176.3 1521.66   196.3 1521.53
   204.4 1520.56   212.4 1520.33   232.4 1521.67   240.4 1523.87   252.4 1531.66
   256.4 1532.38   264.4 1532.29   268.5 1532.79   272.5 1534.75   276.6 1537.94
   280.4 1539.95   288.8 1542.28   307.9 1550.05   317.3 1554.39   343.2 1564.65
#Mann= 4 ,-1,0
       0     .06       0      60      .1       0   94.42    .045       0
   109.8      .1       0
Bank Sta=94.42,109.8
XS Rating Curve= 0 ,0
Exp/Cntr(USF)=0,0
Exp/Cntr=0.3,0.1

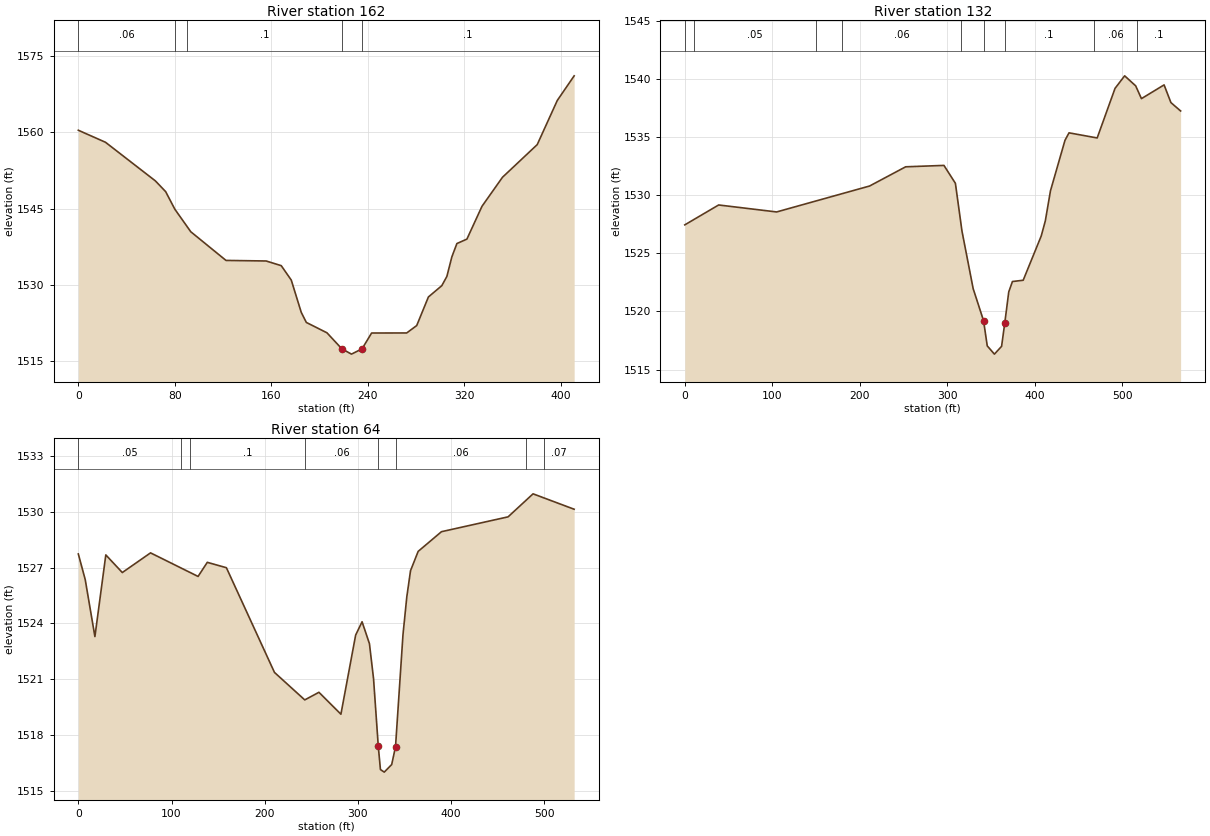
Type RM Length L Ch R = 1 ,162     ,28.9,29.4,29.9
XS GIS Cut Line= 2
2155373.54055935662146.8075176482155260.16694676661751.799454733
#Sta/Elev= 30
       0 1560.42    22.5 1558.06    63.9 1550.46    72.4 1548.35      80  1544.9
    93.2 1540.47   122.4 1534.83   155.7 1534.72   168.2  1533.8   176.5 1530.97
   184.8 1524.61     189 1522.64   206.1  1520.6   218.41517.462   226.4 1516.41
   235.2 1517.45   243.1 1520.56   272.2 1520.57   280.5 1522.03   290.2 1527.65
   301.3 1529.87   305.5 1531.69   309.6 1535.51   313.8 1538.15   322.1 1539.02
   334.6 1545.47   351.6 1551.18   380.4  1557.6     397 1566.27     411 1571.12
#Mann= 5 ,-1,0
       0     .06       0      80     .07       0      90      .1       0
   218.4    .045       0   235.2      .1       0
Bank Sta=218.4,235.2
XS Rating Curve= 0 ,0
Exp/Cntr(USF)=0,0
Exp/Cntr=0.3,0.1

Type RM Length L Ch R = 1 ,132     ,68,68,68
XS GIS Cut Line= 4
2155579.59260128662168.4024914742155347.44663265661954.252334359
2155325.85165882661865.1730673242155401.43406721 661724.80573745
#Sta/Elev= 30
       0 1527.44    38.7 1529.15     105 1528.55   211.3 1530.78   252.5 1532.43
   296.3 1532.55   309.4 1531.01   316.9 1526.91   329.7 1521.96   341.6  1519.2
   345.8 1517.04     354 1516.33   362.2    1517   365.8 1518.98   370.4 1521.68
   374.6 1522.57   386.9 1522.68   407.5 1526.48   412.2 1527.78   418.1 1530.37
   434.7 1534.71   439.3 1535.35   471.5 1534.91   491.9 1539.17   502.9 1540.25
   515.5 1539.39   522.1 1538.29     548 1539.47   555.8 1537.95   566.9 1537.23
#Mann= 9 ,-1,0
       0     .06       0      10     .05       0     150      .1       0
     180     .06       0  315.84      .1       0   341.6    .045       0
   365.8      .1       0  467.49     .06       0  517.49      .1       0
Bank Sta=341.6,365.8
XS Rating Curve= 0 ,0
Exp/Cntr(USF)=0,0
Exp/Cntr=0.3,0.1

Type RM Length L Ch R = 1 ,64      ,,,
XS GIS Cut Line= 5
2155624.27060808662146.6263116682155458.94242783661968.534444933
2155406.54594752661916.510362218 2155398.3556161661853.730248022
2155465.94793499661717.649654862
#Sta/Elev= 30
       0 1527.74     7.4 1526.36    17.8 1523.29    29.5 1527.69    47.2 1526.74
    77.5  1527.8   128.5 1526.53   138.4 1527.29   158.9    1527   210.5 1521.36
     243 1519.88   258.2 1520.29   281.8 1519.11   297.6 1523.37   304.5 1524.09
   312.4 1522.91   316.8 1521.03   321.9 1517.38   324.2 1516.13   328.3 1515.99
   336.3  1516.4   340.4 1517.36   348.4 1523.39   352.5 1525.43   356.5 1526.84
   364.7 1527.88   389.7 1528.94   461.2 1529.74     488 1530.98   532.1 1530.15
#Mann= 8 ,-1,0
       0     .05       0     110     .06       0     120      .1       0
     243     .06       0   321.9    .045       0   340.4     .06       0
  480.15      .1       0  500.15     .07       0
Bank Sta=321.9,340.4
XS Rating Curve= 0 ,0
Exp/Cntr(USF)=0,0
Exp/Cntr=0.3,0.1
LCMann Table=0

Chan Stop Cuts=-1
Use User Specified Reach Order=0
Composite Channel Slope=5